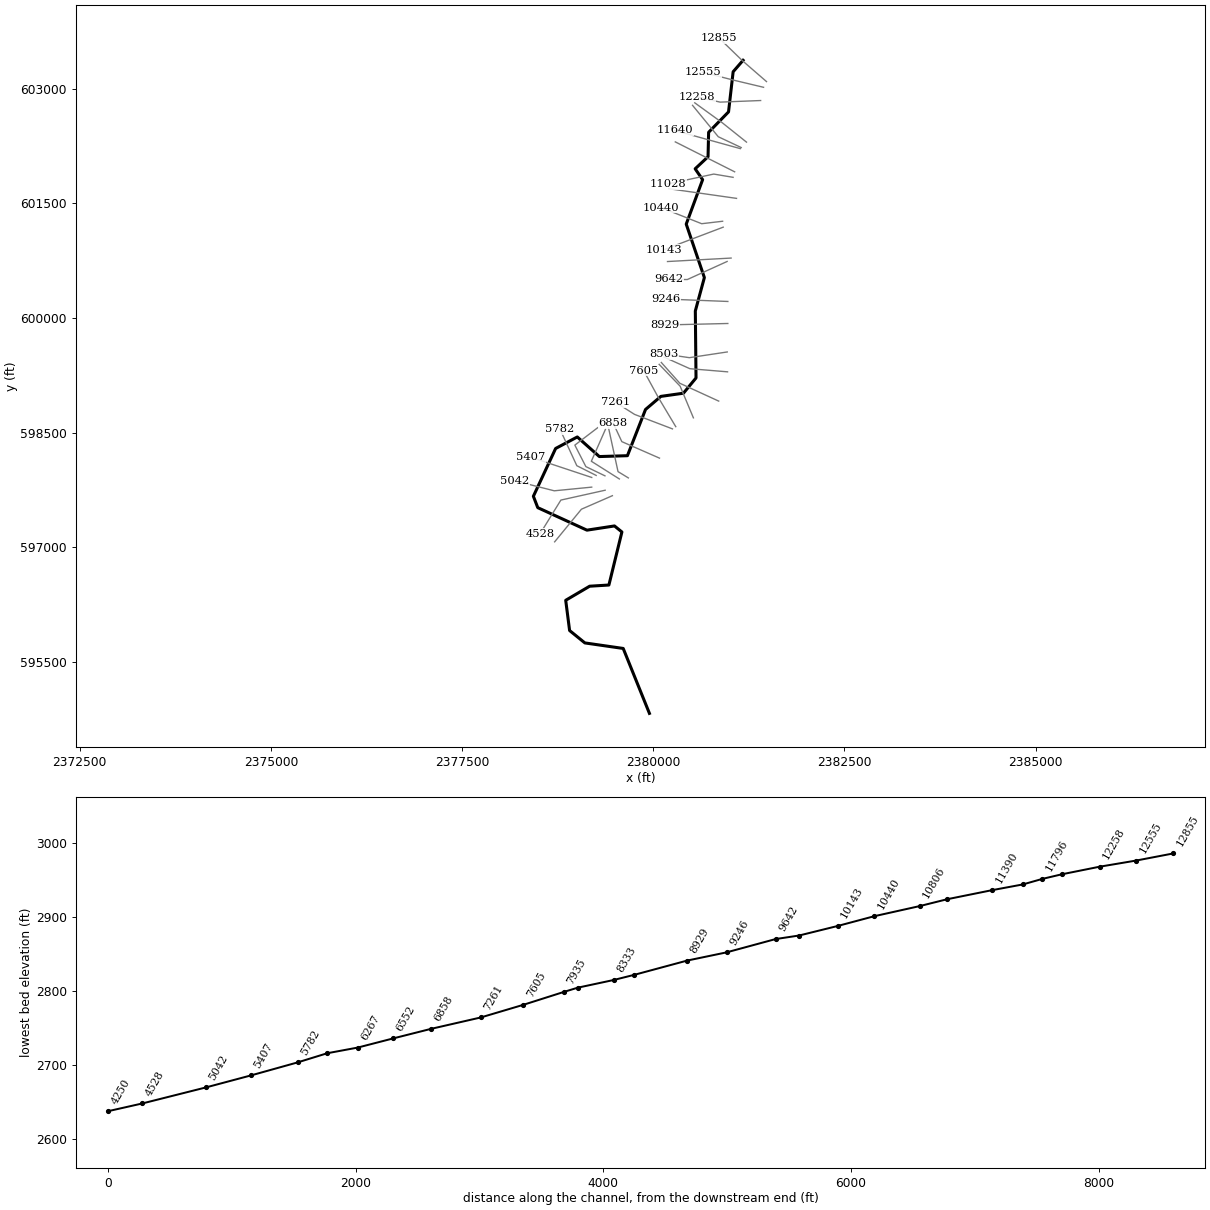
--- SAWMILBR.prj (project) ---

Proj Title=SAWMILBR
Current Plan=p01
Default Exp/Contr=0,0
English Units
Geom File=g01
Flow File=f01
Plan File=p01
BEGIN DESCRIPTION:
Stream Name: Sawmill Branch
Flood Zone: Approximate
Pendleton County, West Virginia
HEC-RAS Version: 5.0.7
Hydrology Method:
Regression equation
END DESCRIPTION:
DSS Export Rating Curves= 0
DSS Export Rating Curve Sorted= 0
DSS Export Volume Flow Curves= 0
DXF OffsetX= 0
DXF OffsetY= 0
DXF ScaleX= 0
DXF ScaleY= 0

--- SAWMILBR.p01 (plan) ---

Plan Title=Floodplain
Program Version=5.07
Short Identifier=Floodplain
Geom File=g01
Flow File=f01
Subcritical Flow
K Sum by GR= 0
Std Step Tol= 0.01
Critical Tol= 0.01
Num of Std Step Trials= 20
Max Error Tol= 0.3
Flow Tol Ratio= 0.001
Split Flow NTrial= 30
Split Flow Tol= 0.02
Split Flow Ratio= 0.02
Log Output Level= 0
Friction Slope Method= 1
Unsteady Friction Slope Method= 2
Unsteady Bridges Friction Slope Method= 1
Parabolic Critical Depth
Global Vel Dist= 0 , 0 , 0
Global Log Level= 0
CheckData=False
Encroach Param=-1 ,0,0, 0
Mapping Interval=1HOUR
Computation Time Step Use Courant=        0
Computation Time Step Use Time Series=    0
Computation Time Step Count To Double=0
Computation Time Step Max Doubling=0
Computation Time Step Max Halving=0
Computation Time Step Residence Courant=0
Run HTab= 0
Run UNet= 0
Run Sediment= 0
Run PostProcess= 0
Run WQNet= 0
Run RASMapper= 0
UNET Theta= 0
UNET Theta Warmup= 0
UNET ZTol= 0
UNET ZSATol= 0
UNET MxIter= 0
UNET Max Iter WO Improvement= 0
UNET MaxInSteps= 0
UNET DtIC= 0
UNET DtMin= 0
UNET MaxCRTS= 0
UNET WFStab= 0
UNET SFStab= 0
UNET WFX= 1
UNET SFX= 1
UNET 1D Methodology=Finite Difference
UNET DSS MLevel= 1
UNET Pardiso=0
UNET DZMax Abort= 0
UNET Use Existing IB Tables= 0
UNET Froude Reduction=False
UNET Froude Limit= 0
UNET Froude Power= 0
UNET D1 Cores= 0
UNET D2 Coriolis=0
UNET D2 Cores= 0
UNET D2 Theta= 1
UNET D2 Theta Warmup= 1
UNET D2 Z Tol= 0.01
UNET D2 Volume Tol= 0.01
UNET D2 Max Iterations= 20
UNET D2 Equation= 0
UNET D2 RampUpFraction=0.1
UNET D2 TimeSlices= 1
UNET D2 BCVolumeCheck=0
UNET D1D2 MaxIter= 0
UNET D1D2 ZTol=0.01
UNET D1D2 QTol=0.1
UNET D1D2 MinQTol=1
Write IC File= 0
Write IC File at Fixed DateTime=0
Write IC File at Sim End=0
Echo Input=False
Echo Parameters=False
Echo Output=False
Write Detailed= 0
HDF Write Warmup=0
HDF Write Time Slices=0
HDF Flush=0
HDF Face Node Velocities=0
HDF Compression= 1
HDF Chunk Size= 1
HDF Spatial Parts= 1
HDF Use Max Rows=0
HDF Fixed Rows= 1
Calibration Method= 0
Calibration Iterations= 20
Calibration Max Change=0.05
Calibration Tolerance=0.2
Calibration Maximum=1.5
Calibration Minimum=0.5
Calibration Optimization Method= 1
WQ AD Non Conservative
WQ ULTIMATE=-1
WQ Max Comp Step=1HOUR
WQ Output Interval=15MIN
WQ Output Selected Increments= 0
WQ Output face flow=0
WQ Output face velocity=0
WQ Output face area=0
WQ Output face dispersion=0
WQ Output cell volume=0
WQ Output cell surface area=0
WQ Output cell continuity=0
WQ Output cumulative cell continuity=0
WQ Output face conc=0
WQ Output face dconc_dx=0
WQ Output face courant=0
WQ Output face peclet=0
WQ Output face adv mass=0
WQ Output face disp mass=0
WQ Output cell mass=0
WQ Output cell source sink temp=0
WQ Output nsm pathways=0
WQ Output nsm derived pathways=0
WQ Output MaxMinRange=-1
WQ Daily Max Min Mean=-1
WQ Daily Range=0
WQ Daily Time=0
WQ Create Restart=0
WQ Fixed Restart=0
WQ System Summary=0
WQ Write To DSS=0
WQ Use Fixed Temperature=0
Sorting and Armoring Iterations= 10
XS Update Threshold= 0.02
Bed Roughness Predictor= 0
Hydraulics Update Threshold= 0.02
Energy Slope Method= 1
Volume Change Method= 1
Sediment Retention Method= 0
XS Weighting Method= 0
Number of US Weighted Cross Sections= 1
Number of DS Weighted Cross Sections= 1
Upstream XS Weight=0
Main XS Weight=1
Downstream XS Weight=0
Number of DS XS's Weighted with US Boundary= 1
Upstream Boundary Weight= 1
Weight of XSs Associated with US Boundary= 0
Number of US XS's Weighted with DS Boundary= 1
Downstream Boundary Weight= 0.5
Weight of XSs Associated with DS Boundary= 0.5
Percentile Method= 0
Sediment Output Level= 3
Mass or Volume Output= 0
Output Increment Type= 1
Profile and TS Output Increment= 1
XS Output Flag= 0
XS Output Increment= 10
Write Gradation File= 0
Read Gradation Hotstart= 0
Write HDF5 File= 1
Write Binary Output= 1
Write DSS Sediment File= 0
SV Curve= 0
Specific Gage Flag= 0

--- SAWMILBR.f01 (steady flow) ---

Flow Title=Flows
Program Version=5.07
Number of Profiles= 6
Profile Names=P100yr,P10yr,P25yr,P50yr,P500yr,P101yr
River Rch & RM=SAWMILBR,Main            ,12855
     579     271     383     478     849     705
River Rch & RM=SAWMILBR,Main            ,11390
     704     328     465     581    1034     857
River Rch & RM=SAWMILBR,Main            ,9642
     783     365     516     646    1151     953
River Rch & RM=SAWMILBR,Main            ,5782
    1404     648     921    1156    2077    1709
Boundary for River Rch & Prof#=SAWMILBR,Main            , 1
Up Type= 0
Dn Type= 3
Dn Slope=0.0408
Boundary for River Rch & Prof#=SAWMILBR,Main            , 2
Up Type= 0
Dn Type= 3
Dn Slope=0.0408
Boundary for River Rch & Prof#=SAWMILBR,Main            , 3
Up Type= 0
Dn Type= 3
Dn Slope=0.0408
Boundary for River Rch & Prof#=SAWMILBR,Main            , 4
Up Type= 0
Dn Type= 3
Dn Slope=0.0408
Boundary for River Rch & Prof#=SAWMILBR,Main            , 5
Up Type= 0
Dn Type= 3
Dn Slope=0.0408
Boundary for River Rch & Prof#=SAWMILBR,Main            , 6
Up Type= 0
Dn Type= 3
Dn Slope=0.0408
DSS Import GetInterval= 0
DSS Import GetPeak= 0
DSS Import FillOption= 0

--- SAWMILBR.g01 (geometry) ---

Geom Title=Geometry
Program Version=5.07

River Reach=SAWMILBR        ,Main
Reach XY= 30
     2381174.146      603371.2132381044.09599999603220.944000021
2380983.78800002602695.8180000192380723.52600002602429.100000009
2380715.90099999 602109.336000012380547.38000003601951.127000004
     2380645.009601808.7709999982380430.60700002601227.288000003
2380667.83399999600527.878000006     2380549.611600090.859000012
2380558.70700002599214.5670000172380394.07700002599014.767000005
2380098.97500002598973.1400000012379898.27900007598801.832000017
2379661.65200004 598197.108000012379294.37400004598185.796000004
2379006.19100001598442.236000016     2378722.796598291.494000018
     2378431.963597666.2639999992378489.24000004597517.192000017
2379132.20500004597222.7530000212379492.42199999597277.895999998
2379589.48199999597199.0200000112379419.57500002596504.890000001
2379167.70300001596489.3030000182378854.71799999596305.063999996
2378905.57600003595909.3620000182379105.14900002 595747.28200002
     2379606.595 595674.892000022379949.40321746594825.348775283

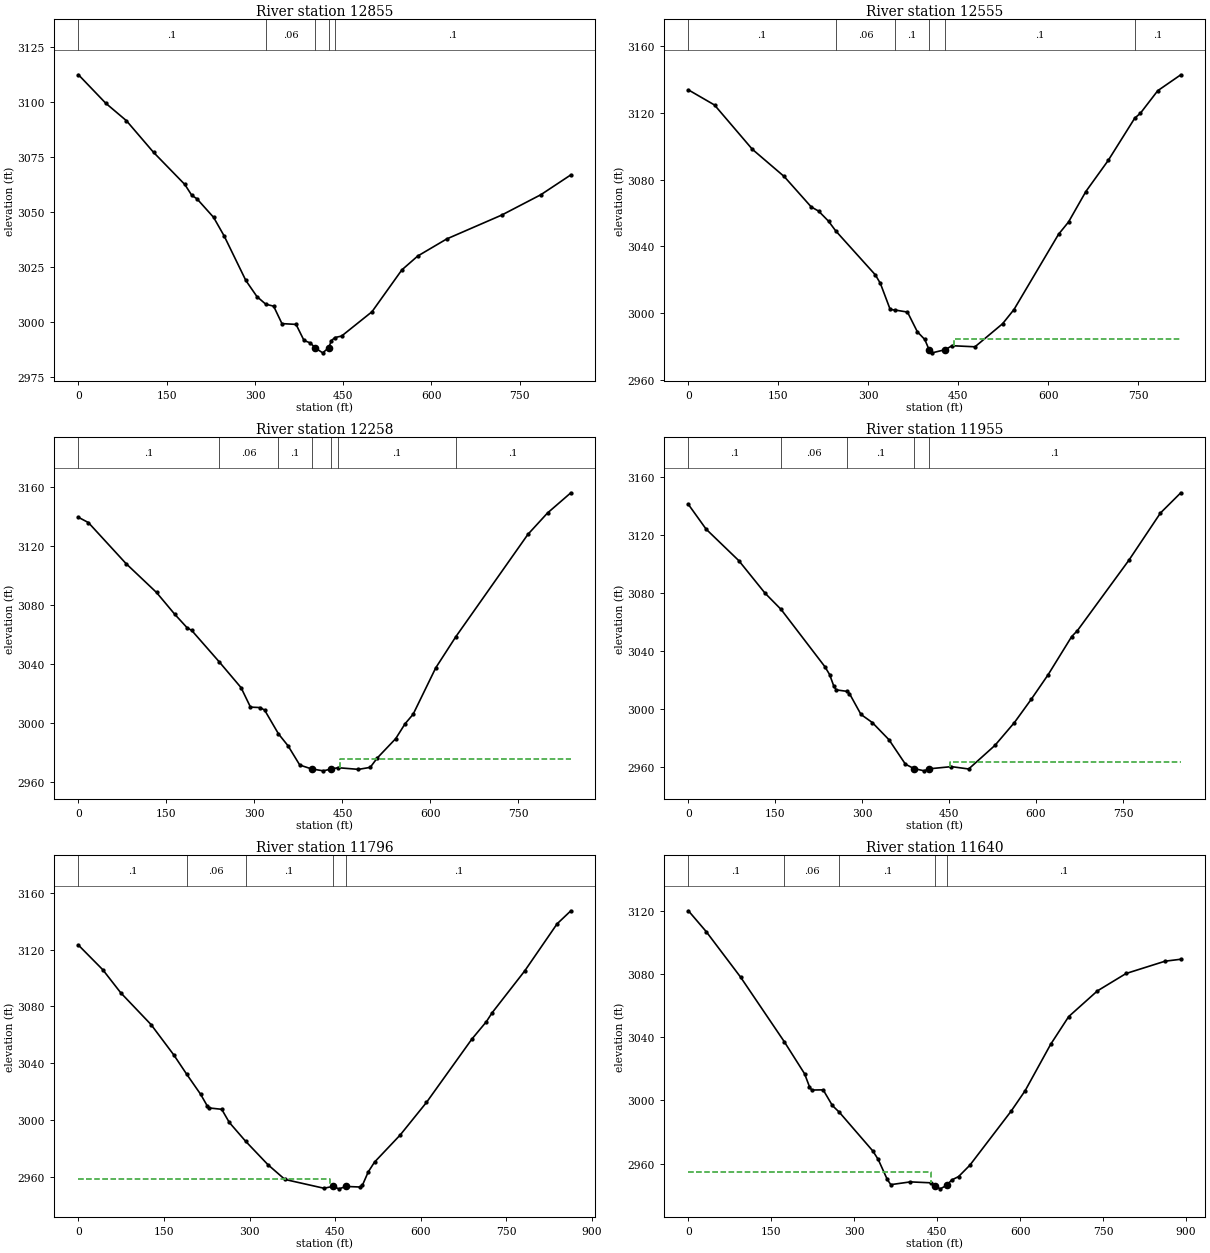
Type RM Length L Ch R = 1 ,12855   ,300,300,300
XS GIS Cut Line= 3
     2381480.314      603092.466      2381166.51      603364.756
2380863.85481696603658.326737392
#Sta/Elev= 30
       0 3112.32    46.4 3099.37    81.5 3091.43   127.6 3077.03   180.7 3062.43
   192.8 3057.41   201.3 3055.93   229.7 3047.45   247.8 3038.92   284.5 3018.74
   303.4  3011.4  318.373007.941   331.8 3007.03   345.9  2999.1   369.9 2998.74
   383.4 2991.45   394.3 2990.28   402.6    2988   415.2  2985.8   425.3 2988.08
     430 2991.36  435.882992.755   447.3 2993.43     499  3004.5   549.8 3023.55
   576.7 3029.84   626.1 3037.63   719.5 3048.48   786.2 3057.77   837.1 3066.78
#Mann= 5 ,-1 , 0
       0      .1       0  318.37     .06       0   402.6    .045       0
   425.3     .06       0  435.88      .1       0
Bank Sta=402.6,425.3
XS Rating Curve= 0 ,0
Exp/Cntr=0.3,0.1

Type RM Length L Ch R = 1 ,12555   ,297,297,297
XS GIS Cut Line= 3
       2381441.9      603017.699     2381044.508      603112.421
2380645.59228025603215.659890914
#Sta/Elev= 30
       0 3133.92    43.5 3124.86   106.5 3098.31   159.5    3082   204.7 3063.72
   217.1 3061.19   233.5 3055.17  245.473049.366   311.6 3022.94   319.9 3017.88
   336.3  3002.2  345.06 3001.84   365.1 3000.65   381.6  2988.8   393.9 2984.23
     4012978.193   406.2  2976.2   428.4 2978.14   439.3 2980.48   477.6 2979.82
   523.6 2993.66   542.6 3002.17   616.9 3047.34   633.5 3054.68   662.4 3072.97
   699.6 3091.59  743.933117.005   753.2 3119.88   782.2 3133.44   820.6 3142.98
#Mann= 6 ,-1 , 0
       0      .1       0  245.47     .06       0  345.06      .1       0
     401    .045       0   428.4      .1       0  743.93      .1       0
#XS Ineff= 2 , 0
                          442.17         2984.43
Permanent Ineff=
       F       F
Bank Sta=401,428.4
XS Rating Curve= 0 ,0
Exp/Cntr=0.3,0.1

Type RM Length L Ch R = 1 ,12258   ,303,303,303
XS GIS Cut Line= 3
     2381403.674      602844.5742380874.38147773602823.585589968
     2380572.511      602892.226
#Sta/Elev= 30
       0 3139.73    16.9 3136.16      81 3108.39     133 3088.79   164.2 3073.96
   185.1 3064.89   193.1 3063.01  239.593041.891   277.1 3024.27   293.2 3011.04
   309.2 3010.75   317.2 3009.09  340.932992.892   357.2 2984.83   377.2 2971.77
   397.2 2969.15   417.3 2967.84   429.9    2969  442.282969.967   477.3 2968.84
   497.3  2970.2   509.3 2976.55   540.8 2989.71   556.7 2999.76   570.4 3006.18
     609 3037.69  642.893058.593   766.1 3128.19   799.5 3142.67   839.3 3156.37
#Mann= 7 ,-1 , 0
       0      .1       0  239.59     .06       0  340.93      .1       0
   397.2    .045       0   429.9      .1       0  442.28      .1       0
  642.89      .1       0
#XS Ineff= 2 , 0
                           445.4         2975.67
Permanent Ineff=
       F       F
Bank Sta=397.2,429.9
XS Rating Curve= 0 ,0
Exp/Cntr=0.3,0.1

Type RM Length L Ch R = 1 ,11955   ,158.8,158.8,158.8
XS GIS Cut Line= 3
2381218.66666082602300.233250787     2380900.752      602554.495
     2380542.292      602814.384
#Sta/Elev= 30
       0 3141.31    30.6 3124.26      87 3102.56   132.3 3080.13  159.963068.933
   235.5 3029.49   243.7 3024.05   250.9 3016.11   255.1 3013.49     2743012.451
   277.9 3010.98   297.8 2996.57   317.5 2990.93   346.2 2979.11   374.6 2962.24
  389.35 2959.24   407.1 2957.68   414.5 2959.02   414.5 2959.03     454 2960.58
   483.7 2958.96   529.1 2975.25   562.7 2990.99   591.8 3007.06   620.8 3023.92
   661.5 3050.24   671.4 3054.35   760.4 3102.96   814.7 3135.41   849.8 3149.34
#Mann= 5 ,-1 , 0
       0      .1       0  159.96     .06       0     274      .1       0
  389.35    .045       0   414.5      .1       0
#XS Ineff= 2 , 0
                          451.06         2963.97
Permanent Ineff=
       F       F
Bank Sta=389.35,414.5
XS Rating Curve= 0 ,0
Exp/Cntr=0.3,0.1

Type RM Length L Ch R = 1 ,11796   ,156.6,156.6,156.6
XS GIS Cut Line= 3
     2381149.796      602229.1282380849.73027148602370.682937921
     2380513.228      602781.532
#Sta/Elev= 30
       0 3123.16    42.7  3105.8    74.1 3089.58   127.2 3067.18     167 3045.82
   189.43032.343     214 3018.09     226 3009.63   228.9 3008.44     251 3007.48
   264.3 2998.22  292.742985.025     332 2968.45   361.7 2958.05   430.3 2951.83
   445.8 2953.18   456.3 2951.43   469.1 2953.11   493.2 2952.72   497.5  2953.9
   507.8 2963.42   518.8 2970.29   563.8 2989.41   609.8 3012.33   689.3 3056.96
   714.7 3069.23     725 3075.61   781.9 3104.99   838.7 3138.21   862.8 3147.39
#Mann= 5 ,-1 , 0
       0      .1       0   189.4     .06       0  292.74      .1       0
   445.8    .045       0   469.1      .1       0
#XS Ineff= 2 , 0
          440.59 2958.34
Permanent Ineff=
       F       F
Bank Sta=445.8,469.1
XS Rating Curve= 0 ,0
Exp/Cntr=0.3,0.1

Type RM Length L Ch R = 1 ,11640   ,249.6,249.6,249.6
XS GIS Cut Line= 2
2381137.63205016602215.052740441 2380279.3894395602453.223840756
#Sta/Elev= 30
       0 3119.94    32.1 3106.81    94.3    3078  173.313037.157   210.2 3016.78
   218.9  3008.7     223  3006.5   243.8 3006.62   260.4 2996.72  273.23 2992.37
   333.7  2967.9   343.4 2962.55   359.6 2950.02   366.1 2946.63   401.5 2948.38
   438.9 2947.79   446.8  2945.7   455.5 2943.98   466.9  2946.1   476.2 2949.57
   488.7 2951.73   509.1 2958.92   583.9 2993.19   609.1 3006.07   655.3 3035.44
   687.9 3052.97   739.8 3069.23   791.7 3080.25   862.3 3088.04   890.7 3089.27
#Mann= 5 ,-1 , 0
       0      .1       0  173.31     .06       0  273.23      .1       0
   446.8    .045       0   466.9      .1       0
#XS Ineff= 2 , 0
          438.11 2954.74
Permanent Ineff=
       F       F
Bank Sta=446.8,466.9
XS Rating Curve= 0 ,0
Exp/Cntr=0.3,0.1

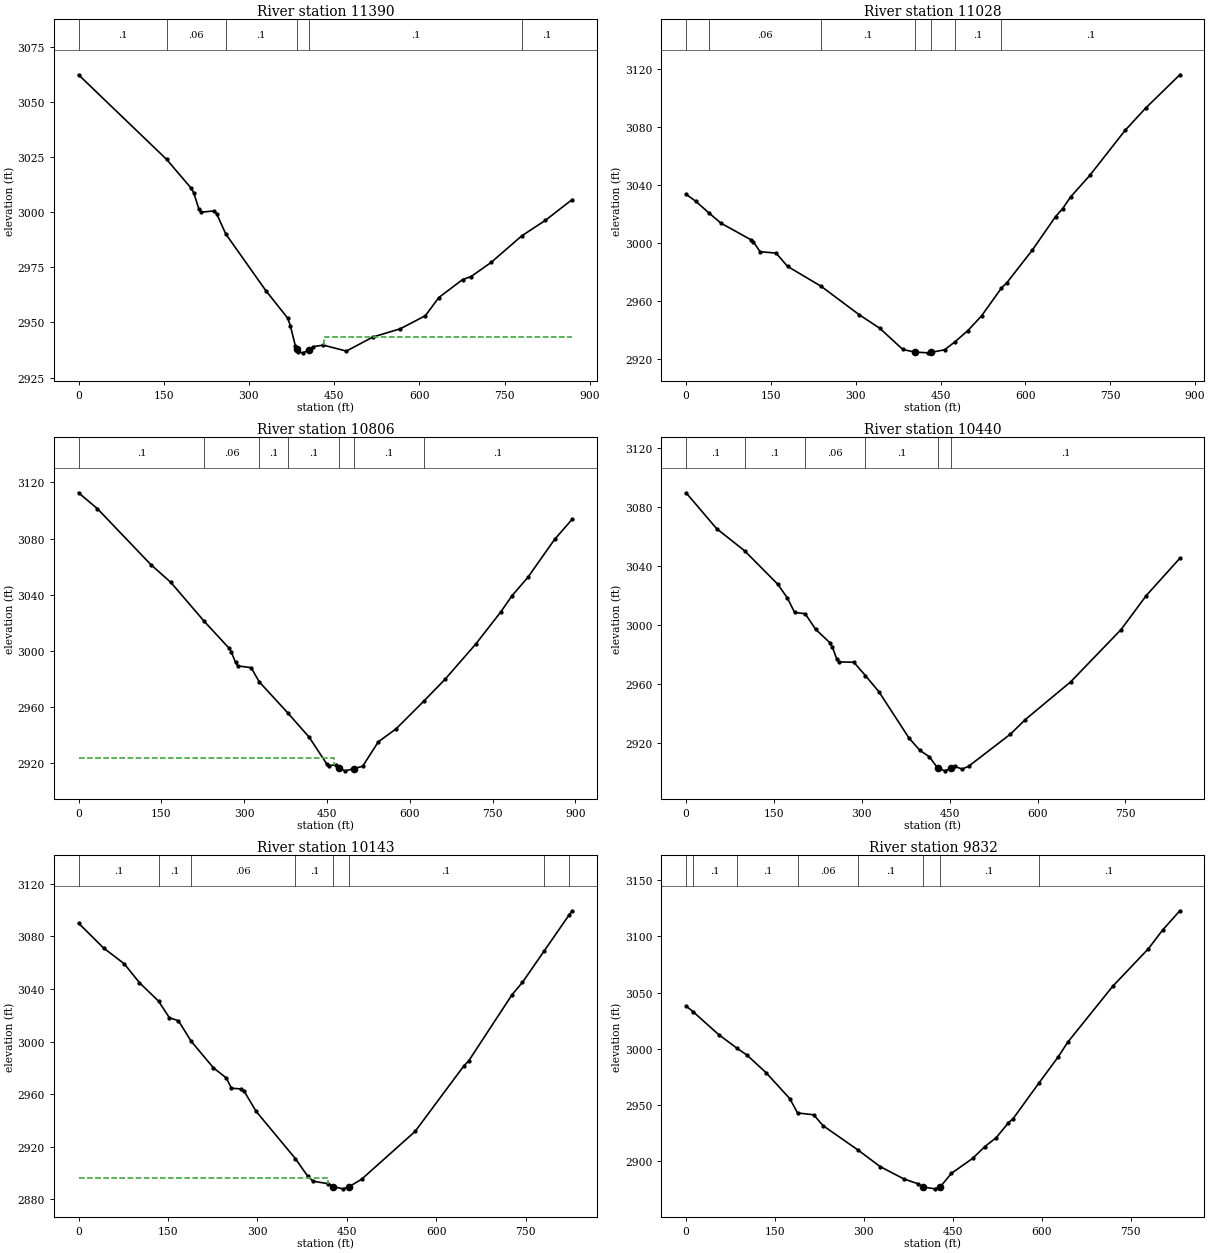
Type RM Length L Ch R = 1 ,11390   ,361.7,361.7,361.7
XS GIS Cut Line= 2
2381063.77382883601911.813265181     2380287.621      602303.316
#Sta/Elev= 30
       0 3062.25  155.123023.888   198.3 3010.84   202.8 3008.77   211.7 3001.55
   216.2 2999.95   238.6 3000.57   243.1 2999.29  259.292990.074   329.8 2964.41
   368.5 2951.87     373 2948.45     382 2939.13   384.1 2937.94   387.2 2936.64
   395.4 2936.22   406.5 2937.67   413.3 2939.05   431.2  2939.7   471.6 2937.02
   518.2 2943.37   566.4 2947.12   610.6 2953.03   634.4 2961.29   676.1 2969.41
   691.1 2970.79   726.3 2977.18  780.152989.191     822 2996.28   869.3 3005.71
#Mann= 6 ,-1 , 0
       0      .1       0  155.12     .06       0  259.29      .1       0
   384.1    .045       0   406.5      .1       0  780.15      .1       0
#XS Ineff= 2 , 0
                          431.79         2943.24
Permanent Ineff=
       F       F
Bank Sta=384.1,406.5
XS Rating Curve= 0 ,0
Exp/Cntr=0.3,0.1

Type RM Length L Ch R = 1 ,11028   ,222.5,222.5,222.5
XS GIS Cut Line= 3
     2381043.682      601839.6052380790.34502146601882.257321255
     2380188.116      601752.337
#Sta/Elev= 30
       0 3033.42    17.2 3028.65   40.313020.597    61.8 3013.52   114.2 3002.17
   119.1 3000.62   130.8 2993.82   159.1  2992.9   179.4 2983.71  238.952969.922
   305.6 2950.48   342.4 2941.01   383.3 2926.34   404.1 2924.58   427.7 2924.03
   432.5 2924.31     457 2926.13     4752931.497   498.4 2939.44   522.5 2949.56
  557.61 2968.74   567.5 2972.56   612.5  2995.1   653.4 3018.12   665.7 3023.49
   679.8 3031.59   713.8 3046.48   776.2 3077.54     813  3093.1     873 3115.95
#Mann= 7 ,-1 , 0
       0      .1       0   40.31     .06       0  238.95      .1       0
   404.1    .045       0   432.5      .1       0     475      .1       0
  557.61      .1       0
Bank Sta=404.1,432.5
XS Rating Curve= 0 ,0
Exp/Cntr=0.3,0.1

Type RM Length L Ch R = 1 ,10806   ,366.2,366.2,366.2
XS GIS Cut Line= 2
2381088.34405769601564.2100214592380203.04953543601690.470904454
#Sta/Elev= 30
       0 3112.62    33.9  3101.4   130.9 3061.54   167.3 3048.81  227.833021.068
   272.3 3002.17   276.4 2999.67   284.4 2991.88   288.5 2989.43   312.7 2988.16
  327.172978.155   378.82956.049   417.8 2938.66   450.1 2919.35   454.1  2918.5
   466.3 2919.02  472.42 2916.53   482.4 2914.75   498.8 2916.22   514.8 2918.09
     543 2935.39   575.4  2944.7  625.182964.243   664.3 2980.09   719.8 3005.13
   765.3 3028.07   785.3 3039.42   813.8 3052.41   862.2 3079.39   894.3 3093.86
#Mann= 7 ,-1 , 0
       0      .1       0  227.83     .06       0  327.17      .1       0
   378.8      .1       0  472.42    .045       0   498.8      .1       0
  625.18      .1       0
#XS Ineff= 2 , 0
           461.9 2923.56
Permanent Ineff=
       F       F
Bank Sta=472.42,498.8
XS Rating Curve= 0 ,0
Exp/Cntr=0.3,0.1

Type RM Length L Ch R = 1 ,10440   ,297,297,297
XS GIS Cut Line= 3
     2380906.449      601264.9242380632.47772706601232.684678088
2380105.52430972601442.196762753
#Sta/Elev= 30
       0 3089.68    52.1 3065.38   99.993050.317   156.8 3027.55   172.9 3018.34
   185.3 3008.51  203.273007.694   221.2 2997.09   245.4 2988.05   249.4  2985.4
   257.4 2976.79   261.5 2974.98   286.3 2974.76  306.082965.763   329.4 2954.67
   380.5 2923.39     399 2915.09   415.5 2910.59   429.8 2902.88   442.1 2901.13
   452.22902.921   458.5 2904.14   471.4 2902.33   482.2 2904.19   553.7    2926
     579 2935.85   656.5 2961.46   742.6 2996.92   785.7 3020.01   842.9 3045.23
#Mann= 6 ,-1 , 0
       0      .1       0   99.99      .1       0  203.27     .06       0
  306.08      .1       0   429.8    .045       0   452.2      .1       0
Bank Sta=429.8,452.2
XS Rating Curve= 0 ,0
Exp/Cntr=0.3,0.1

Type RM Length L Ch R = 1 ,10143   ,310.3,310.3,310.3
XS GIS Cut Line= 2
     2380914.311      601187.5082380140.43415486600893.295654049
#Sta/Elev= 30
       0 3090.15    42.3 3071.12    76.6 3059.24   102.2 3044.81  134.333030.715
   152.1  3018.3   167.6  3015.8  188.863000.239   226.3 2979.96   247.7 2972.37
   256.3 2964.52     273 2963.92   277.7 2962.21   297.8 2946.87  363.762910.815
   384.4 2897.42   393.2 2893.67   418.9  2891.8   427.5 2889.58   443.5 2887.89
   453.1 2889.37   474.5 2895.14   564.4 2931.61   645.7 2981.24   654.3 2985.34
     727 3035.74   744.3 3045.02  780.293068.651  822.613096.412   827.9 3099.58
#Mann= 8 ,-1 , 0
       0      .1       0  134.33      .1       0  188.86     .06       0
  363.76      .1       0   427.5    .045       0   453.1      .1       0
  780.29      .1       0  822.61      .1       0
#XS Ineff= 2 , 0
           417.8 2895.86
Permanent Ineff=
       F       F
Bank Sta=427.5,453.1
XS Rating Curve= 0 ,0
Exp/Cntr=0.3,0.1

Type RM Length L Ch R = 1 ,9832    ,190.3,190.3,190.3
XS GIS Cut Line= 2
      2381017.59      600783.203     2380185.905      600737.722
#Sta/Elev= 30
       0 3038.06   11.473033.081    54.9 3012.57   86.323000.205     103 2994.14
     135 2978.57   175.1 2955.36  187.992942.724   215.2 2941.07   231.2 2931.34
  289.662909.823   327.3 2894.93   367.4  2883.9   391.4 2879.57   399.4  2876.8
   419.5 2875.08   428.4 2876.57   447.6 2888.92   483.6 2902.27   503.6 2912.55
   523.4 2920.79   543.7 2933.89   551.7 2937.62  594.66 2968.97   627.8 2992.73
   643.8 3005.74   719.9 3055.71     780 3089.09     804 3105.77   832.9 3122.87
#Mann= 8 ,-1 , 0
       0      .1       0   11.47      .1       0   86.32      .1       0
  187.99     .06       0  289.66      .1       0   399.4    .045       0
   428.4      .1       0  594.66      .1       0
Bank Sta=399.4,428.4
XS Rating Curve= 0 ,0
Exp/Cntr=0.3,0.1

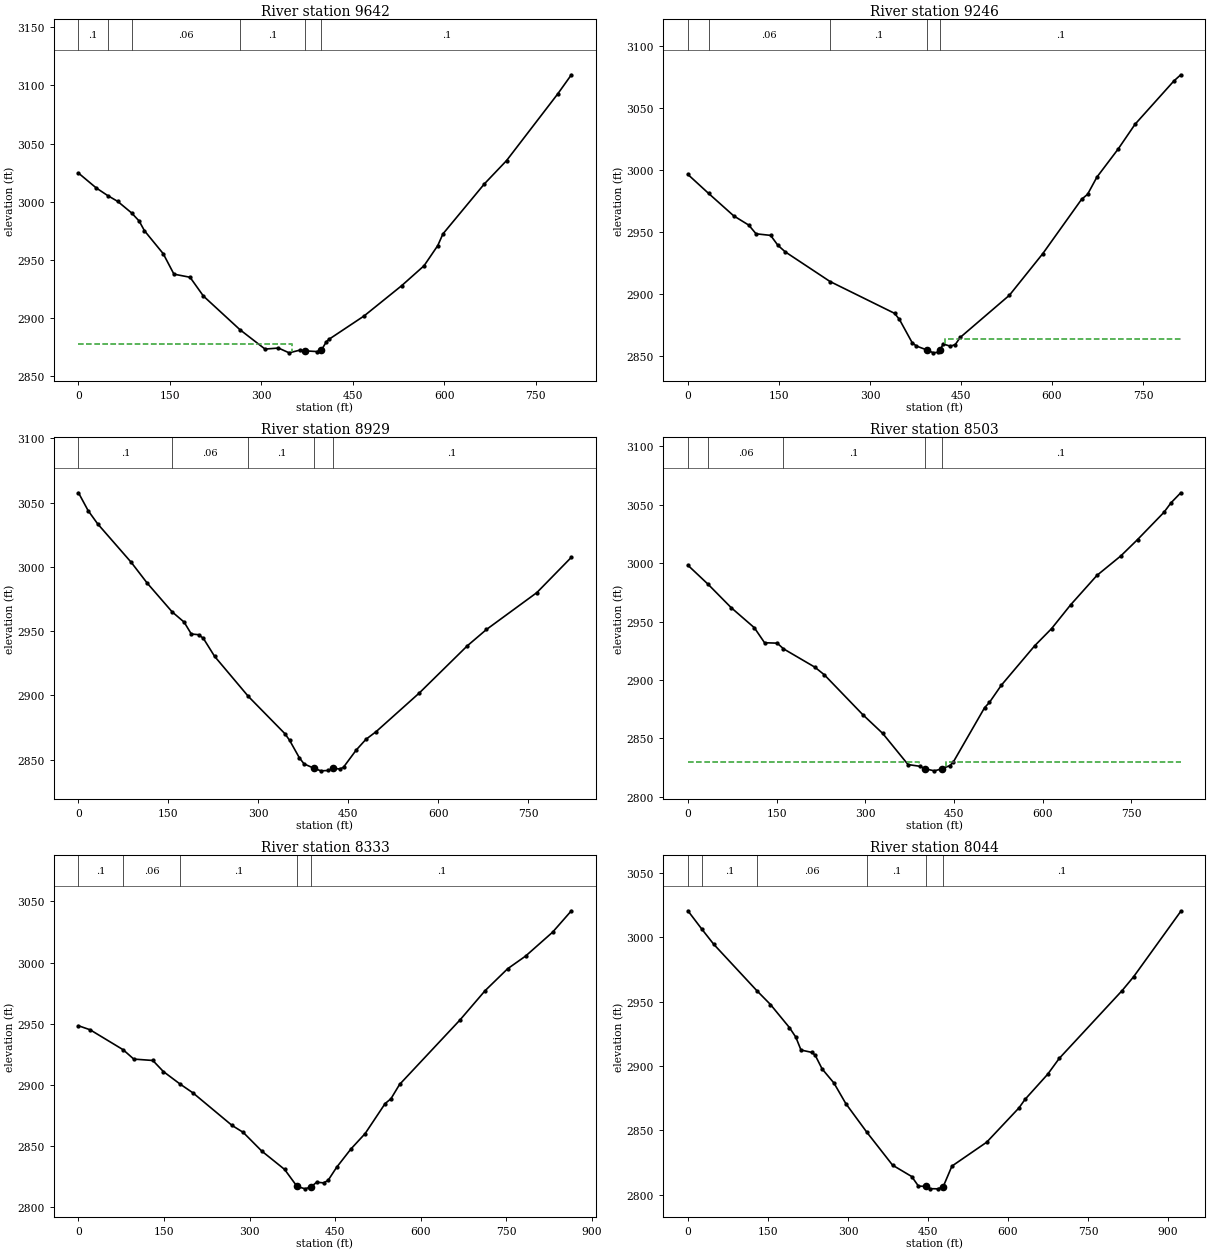
Type RM Length L Ch R = 1 ,9642    ,396,396,396
XS GIS Cut Line= 3
2380965.25942996600738.4930560752380445.17106255600502.296678745
2380208.19363097600502.962690284
#Sta/Elev= 30
       0  3024.6    29.1 3011.86   47.843005.325    64.3 3000.31   86.962990.454
    99.4  2983.5   108.2 2975.09   138.9 2955.42   156.5 2937.84   182.9 2935.16
   204.8 2919.04  264.782890.124   305.9  2873.5   327.9 2874.38   345.4 2870.27
     363 2872.59   371.22871.999   391.3 2871.36   398.1 2872.48   406.4 2879.78
   411.3  2882.1   468.4 2901.99   529.9 2927.94   566.6 2945.04   589.1 2962.38
   597.6 2972.41   665.6 3015.39   701.9 3035.35   785.6 3092.46   808.2 3109.04
#Mann= 6 ,-1 , 0
       0      .1       0   47.84      .1       0   86.96     .06       0
  264.78      .1       0   371.2    .045       0   398.1      .1       0
#XS Ineff= 2 , 0
          349.66  2877.8
Permanent Ineff=
       F       F
Bank Sta=371.2,398.1
XS Rating Curve= 0 ,0
Exp/Cntr=0.3,0.1

Type RM Length L Ch R = 1 ,9246    ,316.9,316.9,316.9
XS GIS Cut Line= 2
2380974.97463097600215.212558503     2380163.481      600247.191
#Sta/Elev= 30
       0 2996.36   34.112981.051    75.6 2962.89   100.3 2955.46   112.3 2948.44
   136.3 2947.16   148.3 2939.16   160.4 2933.86  234.222909.917   340.5 2884.23
   348.5 2879.34   369.6 2860.48   376.5 2857.83  394.02  2854.6   404.5 2852.33
   412.5 2852.91   415.9 2854.89   420.6 2859.48   432.6 2857.66   440.6 2859.06
   448.6 2864.73   529.8 2898.86   584.7  2932.4   648.7  2976.3   658.5  2980.3
   673.9 2994.19   708.8  3016.8   736.8  3036.9   800.7 3071.81   812.1 3076.83
#Mann= 5 ,-1 , 0
       0      .1       0   34.11     .06       0  234.22      .1       0
  394.02    .045       0   415.9      .1       0
#XS Ineff= 2 , 0
                          422.87          2863.2
Permanent Ineff=
       F       F
Bank Sta=394.02,415.9
XS Rating Curve= 0 ,0
Exp/Cntr=0.3,0.1

Type RM Length L Ch R = 1 ,8929    ,426.3,426.3,426.3
XS GIS Cut Line= 2
2380974.76860014 599927.12979867     2380153.168      599907.561
#Sta/Elev= 30
       0 3057.59      16 3043.75      32 3033.39      88 3003.44   114.5 2987.36
  156.142964.955   176.1    2957   188.1 2947.74   200.1 2947.21   208.1 2944.43
   226.9 2930.38  283.222899.181   344.2 2870.19     352 2865.02   368.1 2851.59
   376.1 2846.69   393.3 2843.18   404.1 2841.31   416.1 2841.58   424.1 2843.24
   436.1 2842.74   441.9 2844.16   462.9 2857.39   479.3 2865.84   496.2 2871.78
   568.2 2901.84   648.2 2938.52   680.2 2951.25   764.2 2979.93   821.8 3007.41
#Mann= 5 ,-1 , 0
       0      .1       0  156.14     .06       0  283.22      .1       0
   393.3    .045       0   424.1      .1       0
Bank Sta=393.3,424.1
XS Rating Curve= 0 ,0
Exp/Cntr=0.3,0.1

Type RM Length L Ch R = 1 ,8503    ,169.4,169.4,169.4
XS GIS Cut Line= 3
     2380966.992       599554.552380471.38399825599479.731777467
     2380142.486      599528.473
#Sta/Elev= 30
       0 2998.25   34.052982.026    73.1 2961.98   112.4 2944.73   129.7 2931.87
   151.1 2931.51  161.712926.651   214.7 2910.96   230.8  2904.4   295.6 2870.37
   329.5 2854.19   372.4 2827.49   392.6 2826.01   400.6 2823.95   416.9 2822.12
   429.5 2823.82   442.8 2826.56   448.6 2829.37   501.9 2876.26     510  2880.7
   530.2 2895.48   586.8 2929.38   615.1 2943.93   647.4 2964.35   691.9 2989.56
   732.4  3006.3   760.7  3020.3   805.1 3043.52   817.3 3051.79   833.7 3060.34
#Mann= 5 ,-1 , 0
       0      .1       0   34.05     .06       0  161.71      .1       0
   400.6    .045       0   429.5      .1       0
#XS Ineff= 2 , 0
          391.47 2829.97  437.42         2829.76
Permanent Ineff=
       F       F
Bank Sta=400.6,429.5
XS Rating Curve= 0 ,0
Exp/Cntr=0.3,0.1

Type RM Length L Ch R = 1 ,8333    ,289.6,289.6,289.6
XS GIS Cut Line= 3
2380971.07166655599294.4484440172380478.44233135599335.495555283
     2380140.659      599487.141
#Sta/Elev= 30
       0 2948.36    20.4 2945.06   78.322928.752      97  2921.1   130.4 2919.98
   148.8 2910.95  177.932900.789     201  2893.4   269.3 2866.88   288.9 2861.21
   321.4 2845.94   361.6 2830.88   383.4 2816.97   397.7 2815.03   408.3 2816.77
   417.8 2820.46   429.8 2819.91   437.8 2821.93   452.7 2832.56     478 2847.69
   502.8  2860.2   537.9 2884.76   548.1 2888.69   563.2 2900.36   669.2  2953.1
   713.2 2977.02   752.7 2994.94   784.2  3005.3   831.6 3024.83   864.6 3042.36
#Mann= 5 ,-1 , 0
       0      .1       0   78.32     .06       0  177.93      .1       0
   383.4    .045       0   408.3      .1       0
Bank Sta=383.4,408.3
XS Rating Curve= 0 ,0
Exp/Cntr=0.3,0.1

Type RM Length L Ch R = 1 ,8044    ,108.9,108.9,108.9
XS GIS Cut Line= 3
2380855.46318345 598911.443532912380347.32681999599144.610726672
     2380104.813      599417.017
#Sta/Elev= 30
       0 3020.59   26.223006.298    48.4 2994.61  129.252958.552   154.8  2947.8
   190.2 2929.96   202.2 2922.54     212 2912.46   232.4 2910.63   238.5  2908.5
   251.6 2897.79   273.7 2886.87     296 2870.88  335.322848.687   383.7 2823.06
   419.5 2814.25   432.1 2806.84   446.6 2806.54   454.1 2804.81   468.6 2804.69
   478.6 2806.47   494.9 2822.35     560 2840.89   620.6 2867.57   631.9 2874.15
   674.3 2893.64     696 2905.96   813.8 2958.59   835.3  2969.3   923.8 3020.15
#Mann= 6 ,-1 , 0
       0      .1       0   26.22      .1       0  129.25     .06       0
  335.32      .1       0   446.6    .045       0   478.6      .1       0
Bank Sta=446.6,478.6
XS Rating Curve= 0 ,0
Exp/Cntr=0.3,0.1

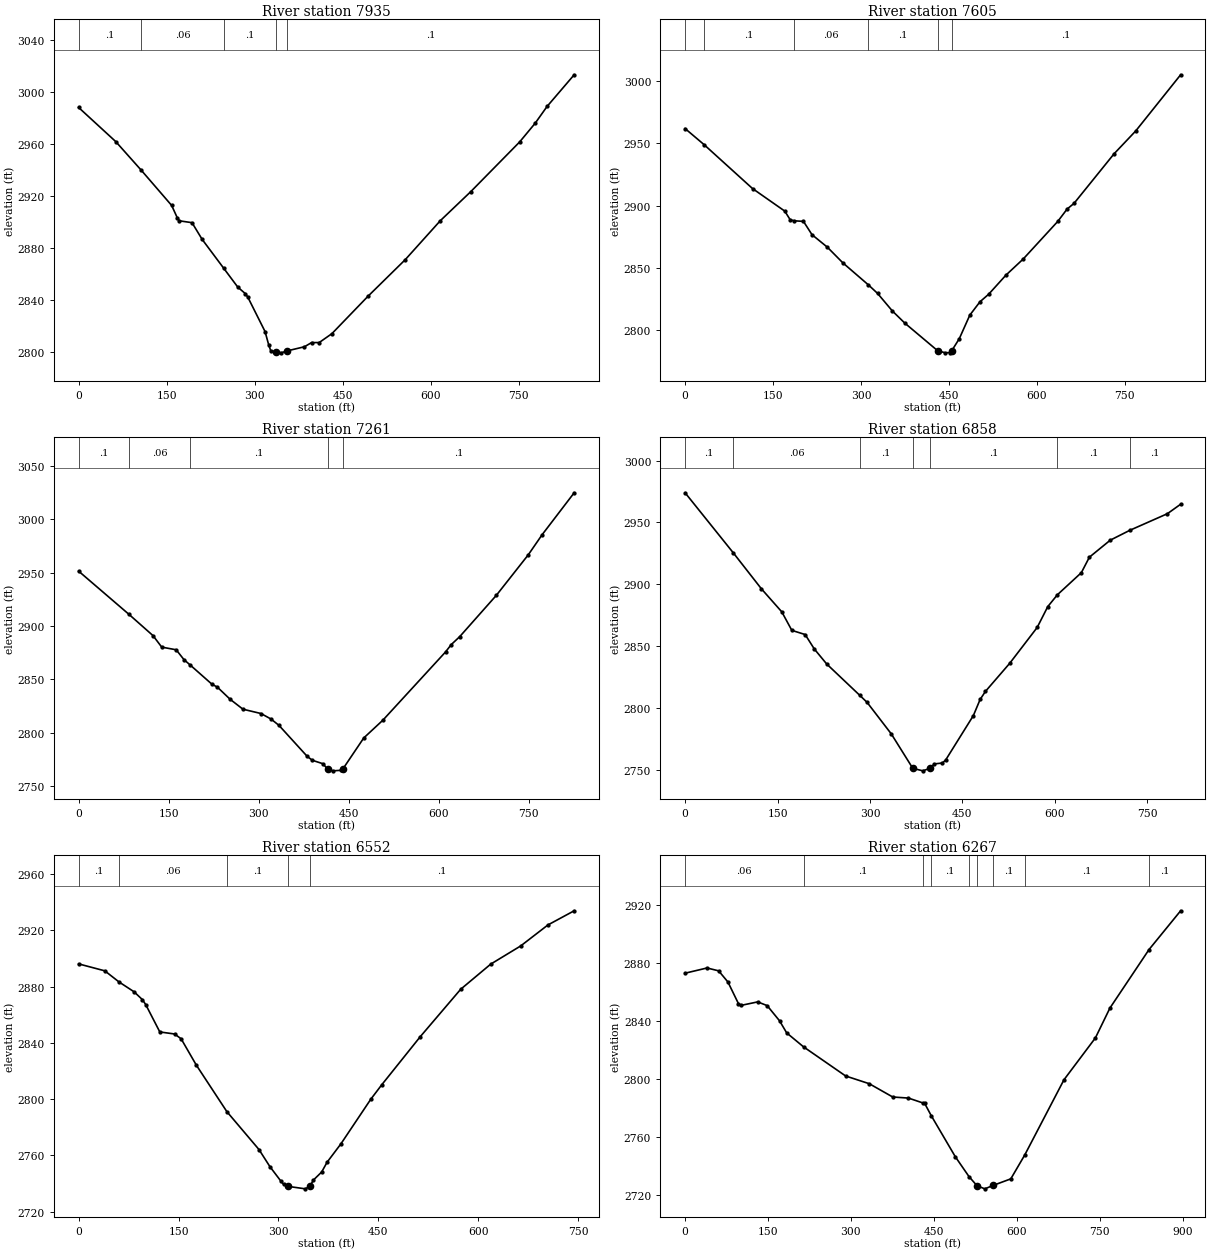
Type RM Length L Ch R = 1 ,7935    ,329.8,329.8,329.8
XS GIS Cut Line= 3
2380524.30929421598692.6006056032380350.99288581599106.552526037
     2380076.693      599392.201
#Sta/Elev= 30
       0 2987.77    63.2 2961.59  106.872939.484   158.6 2912.45     168 2903.13
   171.6 2900.65   193.3  2899.2   210.6 2886.34  247.112864.296   271.3 2849.67
   284.4 2844.56   288.7  2841.7   317.8  2815.5   323.9 2805.48   327.7 2800.48
   336.4 2800.11   345.3 2799.12   355.42800.608     385  2803.8   397.1    2807
   410.1 2807.02   431.8 2813.88   493.6 2842.76   556.7 2870.71   616.6 2900.73
   668.6  2923.1   751.9 2961.31   778.3 2975.67   798.6 2988.58   844.8 3012.93
#Mann= 5 ,-1 , 0
       0      .1       0  106.87     .06       0  247.11      .1       0
   336.4    .045       0   355.4      .1       0
Bank Sta=336.4,355.4
XS Rating Curve= 0 ,0
Exp/Cntr=0.3,0.1

Type RM Length L Ch R = 1 ,7605    ,344.1,344.1,344.1
XS GIS Cut Line= 3
     2380293.682      598576.952     2380067.463      598955.953
     2379874.073      599310.515
#Sta/Elev= 30
       0 2961.95   32.432949.012     115 2913.72     170 2895.58   179.3  2888.6
  186.092887.785   201.9 2887.32   216.5 2876.61   242.8 2866.51     269 2854.01
  312.792836.195   328.3 2829.41   353.6 2815.25   374.9 2805.46   430.8  2783.3
   444.1  2781.6   451.2 2781.86  454.98  2783.4   467.7 2792.96   485.7 2811.95
     503 2822.66   517.8 2828.71   547.2 2844.04   576.9 2857.12   635.7 2887.29
   651.7 2897.26   663.4 2901.78   731.8  2941.7   768.7 2960.05   845.3 3005.21
#Mann= 6 ,-1 , 0
       0      .1       0   32.43      .1       0  186.09     .06       0
  312.79      .1       0   430.8    .045       0  454.98      .1       0
Bank Sta=430.8,454.98
XS Rating Curve= 0 ,0
Exp/Cntr=0.3,0.1

Type RM Length L Ch R = 1 ,7261    ,402.5,402.5,402.5
XS GIS Cut Line= 3
2380250.55976524598547.8996159882379754.85111061598737.616585601
2379505.82217109598895.942645872
#Sta/Elev= 30
       0 2951.38   84.022910.894     124 2891.03   138.5 2880.29   162.6  2877.8
   175.6 2868.55  185.462863.785   222.5 2845.42   231.1 2842.93   252.5 2831.48
   273.9 2822.19   303.9 2818.16   320.6 2813.02   333.9 2807.08     381 2778.04
   389.5 2774.41   406.7 2771.26   415.2 2766.19   423.8 2764.53   436.7 2765.02
   440.9 2766.69   475.2 2795.29   507.1 2811.94   611.5 2875.77     621 2882.64
   635.2 2890.13   696.2 2928.76   749.4 2966.67   772.6 2985.56   825.9 3024.71
#Mann= 5 ,-1 , 0
       0      .1       0   84.02     .06       0  185.46      .1       0
   415.2    .045       0   440.9      .1       0
Bank Sta=415.2,440.9
XS Rating Curve= 0 ,0
Exp/Cntr=0.3,0.1

Type RM Length L Ch R = 1 ,6858    ,306.2,306.2,306.2
XS GIS Cut Line= 3
     2380081.203       598165.162379588.37746619598381.128975304
2379476.39291599598622.393299796
#Sta/Elev= 30
       0 2973.99   78.152925.451   123.9 2896.28   156.9  2877.7   173.2 2862.72
   194.8 2859.36   209.7 2847.65   229.8 2835.52  283.282810.261   295.3 2804.51
   334.6 2778.99   369.5 2751.15   385.8 2749.13   397.9  2751.3   404.5 2754.73
   417.6 2755.47   422.9 2757.96   467.8 2793.85   478.7 2806.83   487.4 2813.39
   526.8 2836.12   571.3 2865.06   588.5 2881.93  604.152891.532     643 2909.39
     656 2921.89   689.9 2935.66  721.432943.592   782.6 2957.07   804.1 2964.73
#Mann= 7 ,-1 , 0
       0      .1       0   78.15     .06       0  283.28      .1       0
   369.5    .045       0   397.9      .1       0  604.15      .1       0
  721.43      .1       0
Bank Sta=369.5,397.9
XS Rating Curve= 0 ,0
Exp/Cntr=0.3,0.1

Type RM Length L Ch R = 1 ,6552    ,284.8,284.8,284.8
XS GIS Cut Line= 3
2379673.77723865597906.4226829392379538.83285668597988.743716598
2379414.63917794598561.315871456
#Sta/Elev= 30
       0 2896.22    39.3 2891.28   60.682883.358    83.2 2876.39    95.7 2870.82
   100.7 2867.31   121.9 2847.81   144.1 2846.36   153.9 2842.94   176.6  2824.3
  222.572791.124   270.8 2764.16   287.2    2752   303.5 2741.81   307.6  2739.5
   314.7 2737.95   340.4 2736.22   347.2  2738.1   352.6  2742.5   364.9  2748.2
   373.1 2755.21   393.6 2768.09   438.6 2799.93     455 2810.18   513.1 2844.55
   573.6 2878.17   618.7 2896.05   663.7 2908.99   704.6 2923.92     744    2934
#Mann= 5 ,-1 , 0
       0      .1       0   60.68     .06       0  222.57      .1       0
   314.7    .045       0   347.2      .1       0
Bank Sta=314.7,347.2
XS Rating Curve= 0 ,0
Exp/Cntr=0.3,0.1

Type RM Length L Ch R = 1 ,6267    ,245.8,245.8,245.8
XS GIS Cut Line= 3
2379556.28841591597892.6535320742379189.88977429598124.317215789
2379376.92061781598548.018930768
#Sta/Elev= 30
       0 2873.04    39.7 2876.65    60.7 2874.67    77.5 2866.95    96.5 2852.01
   101.5  2850.8   131.4  2853.2   148.5 2850.62   170.9 2840.12   183.8 2831.76
  214.232822.137   290.5 2801.96   333.3 2796.61   375.7 2787.43   404.1 2786.69
  430.172783.333   433.5 2782.96  445.612774.362   488.8  2746.2  513.562732.461
   528.1  2726.1   542.3 2723.93   557.4 2726.31   589.3 2730.83  614.522747.322
   685.5 2799.34   742.4 2828.31   768.6  2848.9  839.442889.403   896.6  2916.2
#Mann= 9 ,-1 , 0
       0     .06       0  214.23      .1       0  430.17      .1       0
  445.61      .1       0  513.56      .1       0   528.1    .045       0
   557.4      .1       0  614.52      .1       0  839.44      .1       0
Bank Sta=528.1,557.4
XS Rating Curve= 0 ,0
Exp/Cntr=0.3,0.1

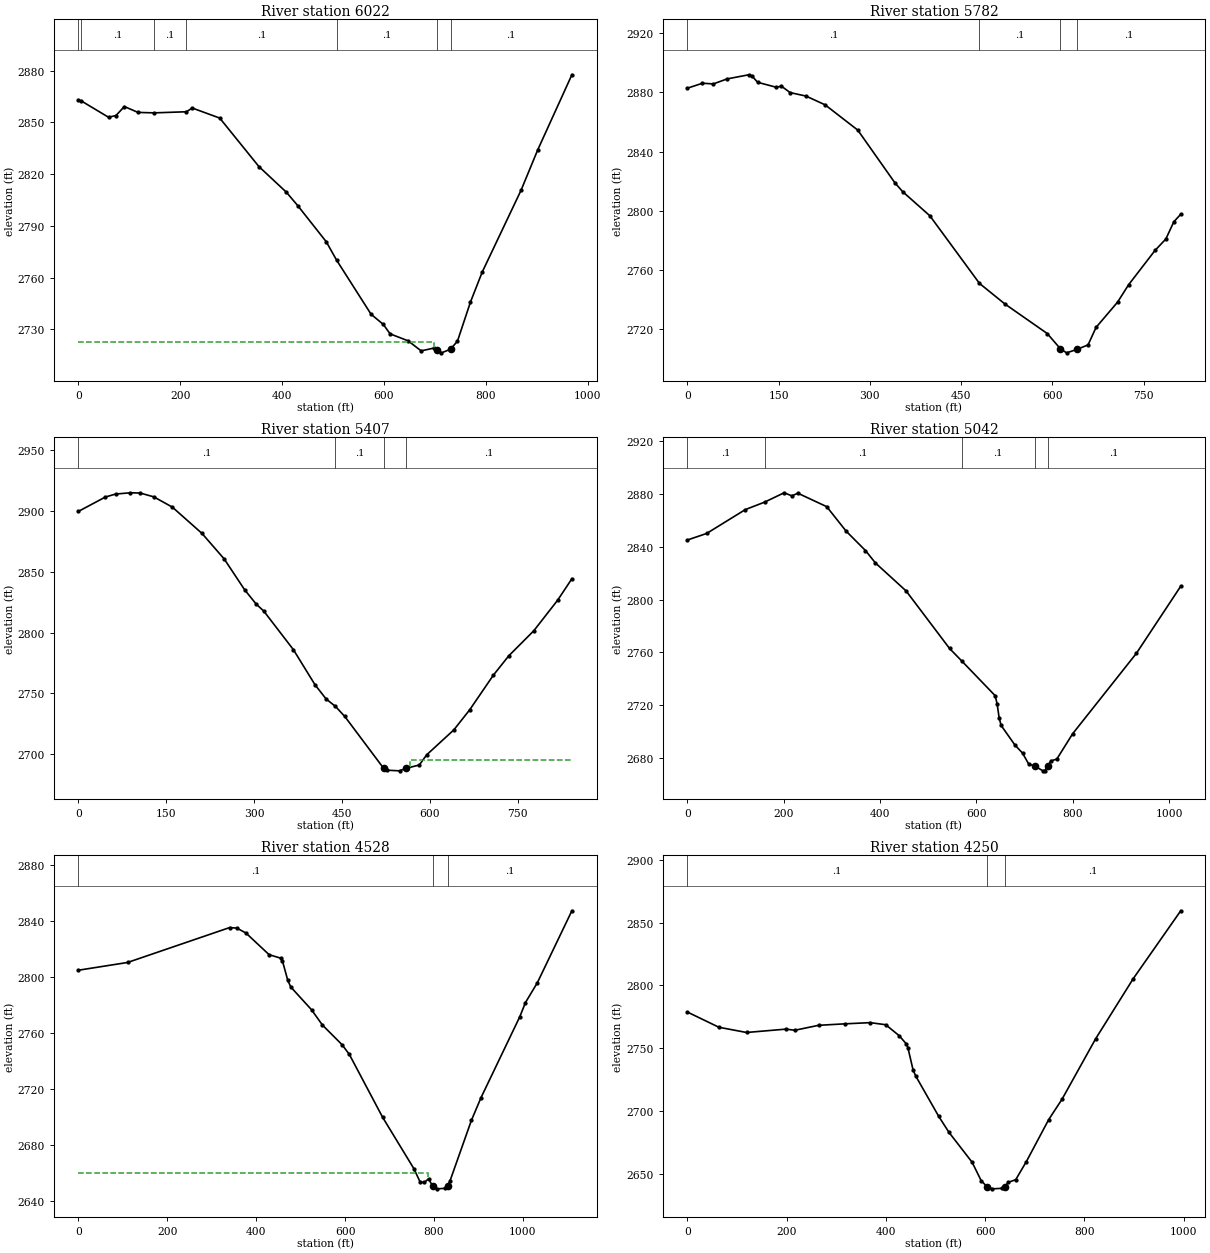
Type RM Length L Ch R = 1 ,6022    ,240,240,240
XS GIS Cut Line= 4
2379368.02314617597933.5869299152379118.15130886598054.486335265
2378974.20028395598335.4345765332379273.06445648598563.468867453
#Sta/Elev= 30
       0 2862.78    4.882862.601    59.2 2852.99    73.8 2854.01    90.3 2859.21
     117 2855.81  148.542855.539  212.162856.184   223.6 2858.35   277.6 2852.51
   354.4 2824.42   408.4 2809.52   430.9 2801.67   486.8 2780.76     5072770.126
   574.8 2738.69     599 2732.75   612.1 2727.32   647.5 2723.27   673.2 2717.44
   698.9 2719.11   704.5 2717.97   713.1  2716.3   730.8  2718.4   744.5 2723.11
     770 2745.77     793 2763.11   869.3 2810.59   902.3 2834.19   969.2 2877.64
#Mann= 7 ,-1 , 0
       0     .06       0    4.88      .1       0  148.54      .1       0
  212.16      .1       0     507      .1       0   704.5    .045       0
   730.8      .1       0
#XS Ineff= 2 , 0
          699.26  2722.4
Permanent Ineff=
       F       F
Bank Sta=704.5,730.8
XS Rating Curve= 0 ,0
Exp/Cntr=0.3,0.1

Type RM Length L Ch R = 1 ,5782    ,374.6,374.6,374.6
XS GIS Cut Line= 3
2379253.06324134597938.9415724262378999.95500846598066.266297133
2378778.84179375598545.110719748
#Sta/Elev= 30
       0 2882.77      25 2886.15    42.9 2885.69    65.3 2889.06   101.1 2891.87
     106 2891.23   115.6 2886.79   145.9 2883.47   154.8 2884.14     169 2879.84
   195.1 2877.47   226.5 2871.56   280.2 2854.45   341.3 2818.76     354 2812.84
   398.6 2796.55  480.132750.845   521.9 2736.94   591.5 2716.95   613.2 2706.59
   623.3 2703.91   640.4 2706.25   658.5 2709.28   671.7 2721.12     707 2738.18
   725.1 2749.92   768.7 2773.21   786.3 2780.84   799.5 2792.55   810.8 2797.58
#Mann= 4 ,-1 , 0
       0      .1       0  480.13      .1       0   613.2    .045       0
   640.4      .1       0
Bank Sta=613.2,640.4
XS Rating Curve= 0 ,0
Exp/Cntr=0.3,0.1

Type RM Length L Ch R = 1 ,5407    ,365.3,365.3,365.3
XS GIS Cut Line= 2
2379194.91581061597912.4027730562378395.52264013598177.921179937
#Sta/Elev= 30
       0 2899.53      46 2911.32    63.4 2913.77    88.7 2914.82   105.6  2914.6
   128.7 2911.47   160.3 2903.05   210.9 2881.47   248.9 2860.44   283.7 2835.18
   303.7 2823.27   316.3 2817.73   366.9 2786.01   403.9 2757.11   422.9 2745.43
   438.7  2739.4   454.6 2731.16     521 2688.52     527 2686.98   548.1 2686.46
     559  2688.5   581.8 2691.24   594.5 2699.63   640.8 2720.09   667.8 2736.53
   708.3 2765.05   734.7 2780.99   777.3 2801.51   817.9 2826.55   842.3 2844.22
#Mann= 4 ,-1 , 0
       0      .1       0   438.7      .1       0     521    .045       0
     559      .1       0
#XS Ineff= 2 , 0
                          566.58         2695.18
Permanent Ineff=
       F       F
Bank Sta=521,559
XS Rating Curve= 0 ,0
Exp/Cntr=0.3,0.1

Type RM Length L Ch R = 1 ,5042    ,514,514,514
XS GIS Cut Line= 3
2379194.74060121597785.7786815122378705.09491476 597737.74072852
2378189.39389969597868.620439496
#Sta/Elev= 30
       0 2845.08    40.2 2850.08   120.6 2868.19  160.582873.836     201 2880.91
     217 2878.61   229.6 2880.56   289.4 2870.39   329.6 2851.86   369.8 2837.14
   390.6 2827.68   454.2 2806.49   544.2 2762.95  569.172753.605   638.9 2727.15
     643 2720.92   647.1 2710.55   651.2 2704.63   680.1 2689.67   695.7 2683.65
   708.8 2675.14   721.4 2673.83   737.9 2670.19     742 2670.42   748.22674.088
   754.4 2677.71   766.8 2679.08   799.8 2698.35   931.9  2759.2    1024  2810.1
#Mann= 5 ,-1 , 0
       0      .1       0  160.58      .1       0  569.17      .1       0
   721.4    .045       0   748.2      .1       0
Bank Sta=721.4,748.2
XS Rating Curve= 0 ,0
Exp/Cntr=0.3,0.1

Type RM Length L Ch R = 1 ,4528    ,277.4,277.4,277.4
XS GIS Cut Line= 3
2379370.63392022597745.3438787042378791.58059622597616.393435037
2378519.87876604597176.541826685
#Sta/Elev= 30
       0 2804.93   110.5 2810.46     340  2835.4   356.4 2835.06   376.9 2831.54
   428.9 2816.07   454.8 2813.56   458.9 2811.74   471.1 2797.59   477.9 2792.89
   524.4 2776.67     549  2765.7   593.2 2751.65   609.5 2744.71   684.3 2699.79
   754.9  2662.9     769 2653.27   778.4 2653.25   787.8 2655.71   797.2 2650.37
   807.1 2648.56   825.4 2648.93   830.8  2650.8   836.2 2654.41   884.1  2697.5
   905.9 2713.88   993.1 2771.72  1005.8 2781.83  1032.3 2795.85  1110.2 2847.44
#Mann= 3 ,-1 , 0
       0      .1       0   797.2    .045       0   830.8      .1       0
#XS Ineff= 2 , 0
          787.29 2660.11
Permanent Ineff=
       F       F
Bank Sta=797.2,830.8
XS Rating Curve= 0 ,0
Exp/Cntr=0.3,0.1

Type RM Length L Ch R = 1 ,4250    ,306.4,306.4,306.4
XS GIS Cut Line= 3
2379465.14143982597673.7648901342379060.26589223597496.923224634
     2378710.065       597069.85
#Sta/Elev= 30
       0 2778.87    63.7 2766.72   119.4 2762.55     199 2765.23   216.7 2764.32
   264.5 2768.26   316.8 2769.42   368.6 2770.39   399.8 2768.72   426.9    2760
   441.5 2753.37   444.4 2750.57   454.8 2732.91     460 2728.05   506.5 2695.82
   527.2 2683.06   573.8 2659.28   592.1 2644.59   603.5 2639.91   614.5 2638.09
   634.8 2638.52   640.4 2639.91   646.1 2643.18   661.7 2645.38   683.1 2659.78
   728.1 2693.21   754.8 2709.32   822.7 2757.56   898.4  2805.4   994.1 2859.43
#Mann= 3 ,-1 , 0
       0      .1       0   603.5    .045       0   640.4      .1       0
Bank Sta=603.5,640.4
XS Rating Curve= 0 ,0
Exp/Cntr=0.3,0.1