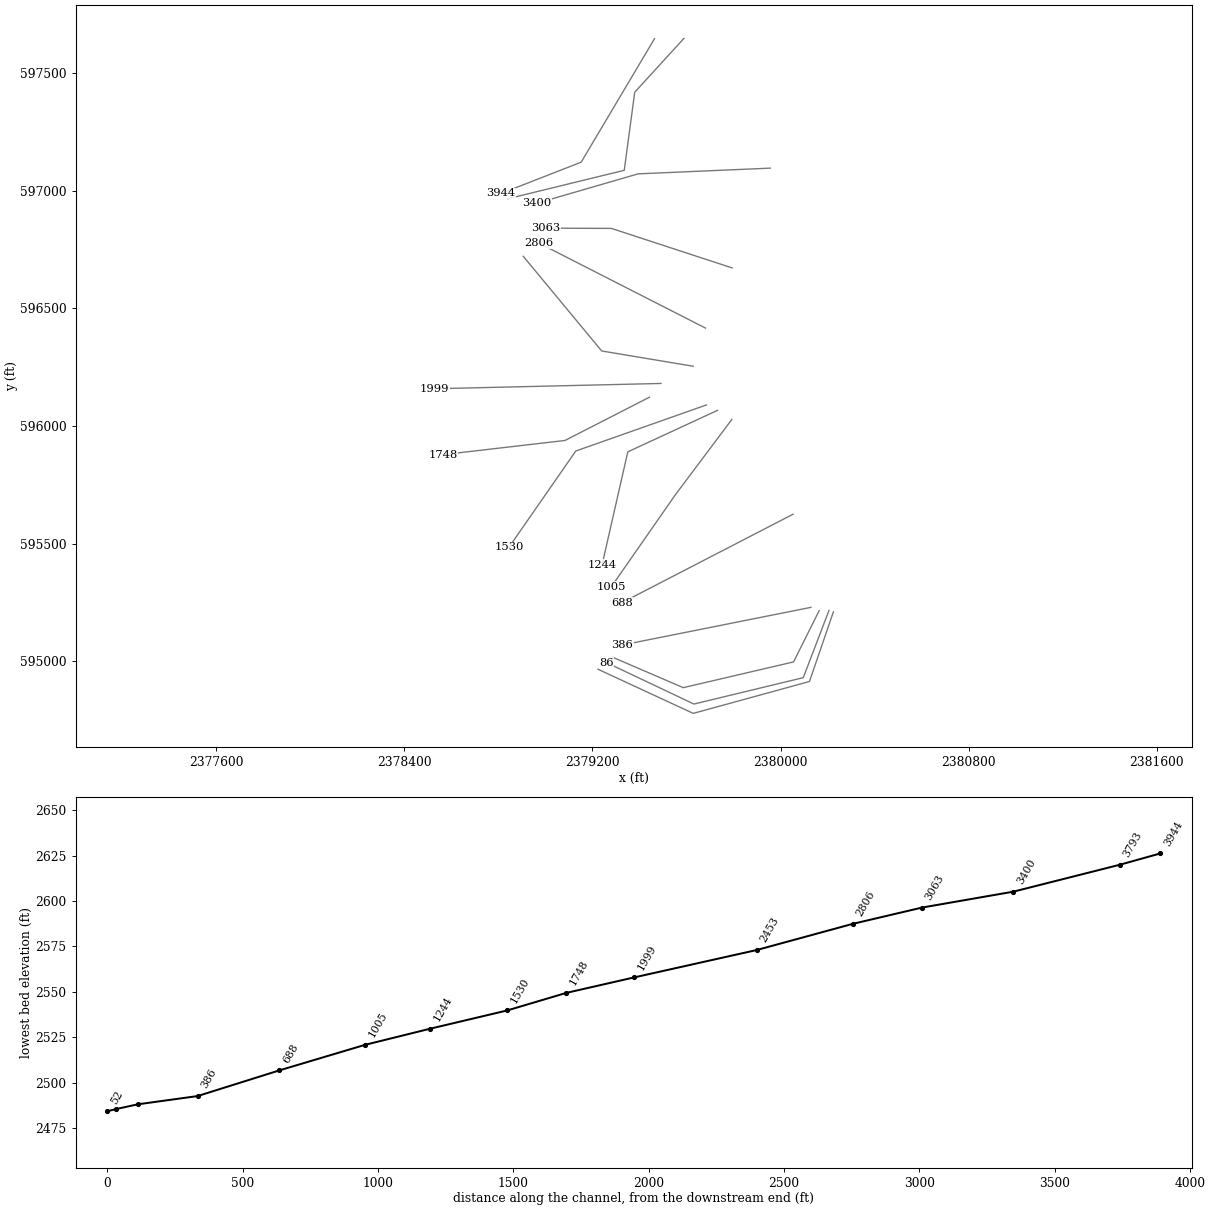
HEC-RAS study SAWMILBR.prj: SAWMILBR

--- SAWMILBR.g01 (geometry) --- (continued)

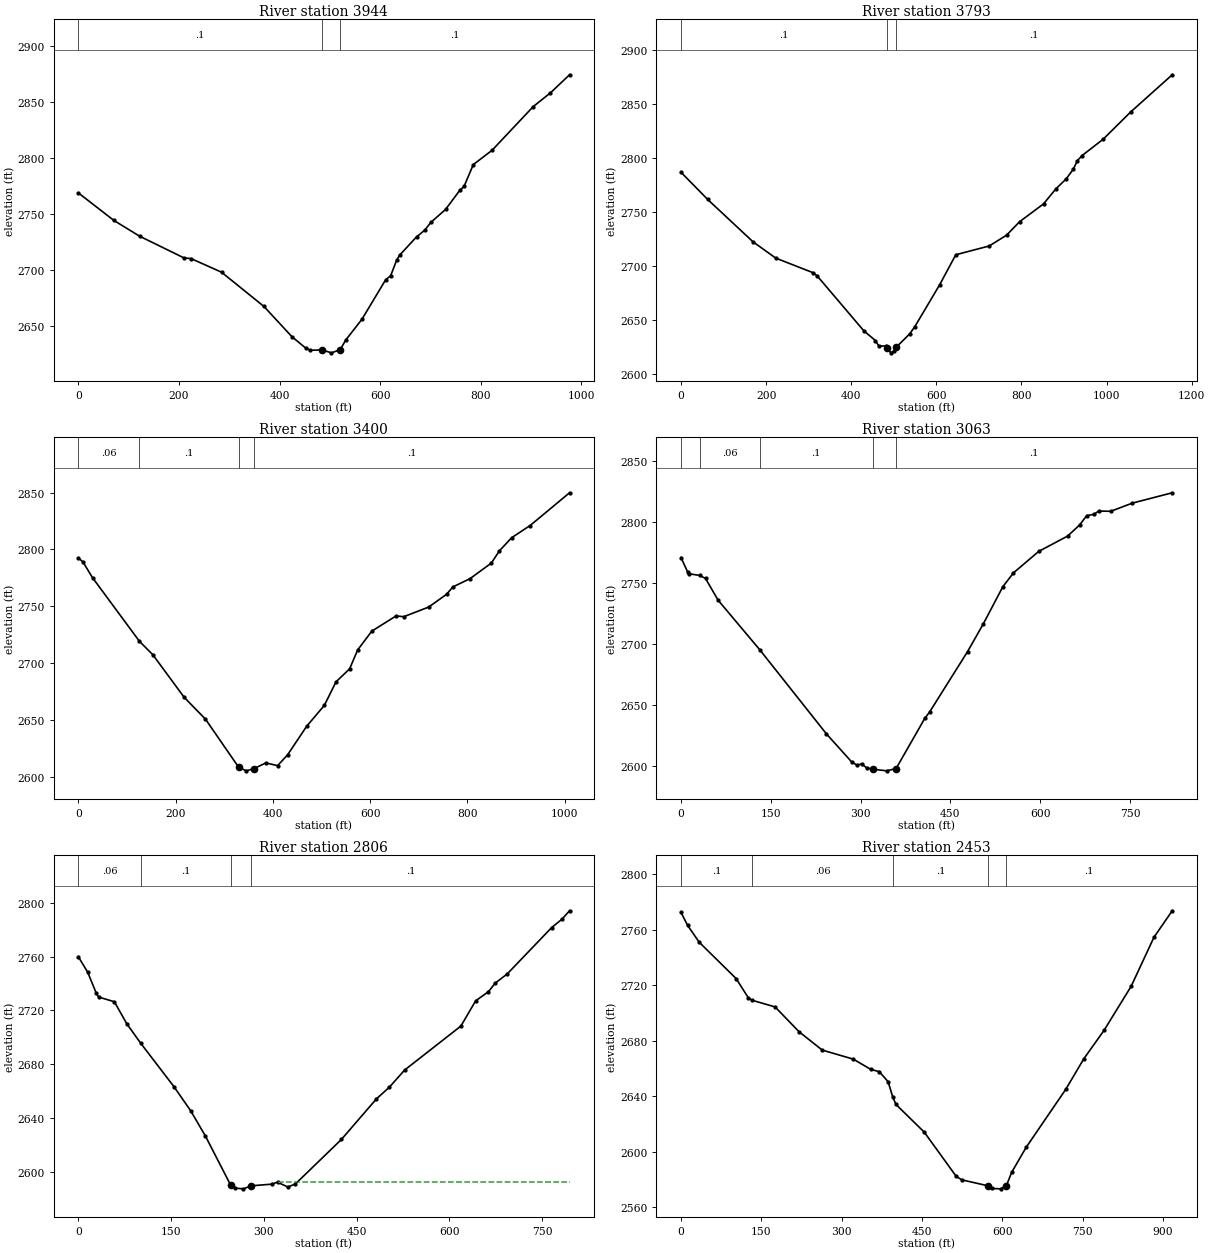
Type RM Length L Ch R = 1 ,3944    ,150.8,150.8,150.8
XS GIS Cut Line= 3
2379463.83260436597647.6406520482379151.77668713597122.240117858
2378811.41833041596989.271970536
#Sta/Elev= 30
       0 2769.18    70.7 2744.55   121.8 2730.48   210.2 2711.03   224.2 2710.46
   284.7  2698.3   369.1 2667.67   424.6  2640.7   452.1 2630.48   461.5 2628.56
   484.7 2628.82   503.3 2626.25   520.9 2629.16   531.2 2637.43   563.8 2656.22
   611.1 2691.64   620.8 2695.02     633 2709.26   639.2 2713.75   672.3 2729.81
   688.6 2735.82   700.9 2742.82   730.2 2754.44   758.2 2771.36   766.8 2774.94
   785.2 2794.43   822.6 2807.25   904.2 2846.21   938.6 2858.55   976.5 2874.67
#Mann= 3 ,-1 , 0
       0      .1       0   484.7    .045       0   520.9      .1       0
Bank Sta=484.7,520.9
XS Rating Curve= 0 ,0
Exp/Cntr=0.3,0.1

Type RM Length L Ch R = 1 ,3793    ,393,393,393
XS GIS Cut Line= 4
2379589.05353666597649.0761623942379379.59053946597419.816206089
2379335.03215365597087.6341548162378841.09693966596966.941361205
#Sta/Elev= 30
       0 2786.92    62.6  2761.8   169.5 2722.52   222.8 2707.52   310.5 2694.01
     320 2691.11   429.5 2640.39   456.8 2631.34   464.8 2626.38     481 2626.19
     485 2624.44   493.1 2619.98   501.2 2621.72   505.2 2624.94   537.5 2637.57
   549.6  2644.3   607.5 2682.68   645.7 2710.64   724.2 2718.74     765 2728.73
   795.5 2741.13   851.9 2757.65   880.7 2771.48   904.7  2780.6   921.9 2789.68
   931.1 2797.49   942.5 2802.35   991.9 2817.39  1056.9 2842.71  1154.2 2876.97
#Mann= 3 ,-1 , 0
       0      .1       0     485    .045       0   505.2      .1       0
Bank Sta=485,505.2
XS Rating Curve= 0 ,0
Exp/Cntr=0.3,0.1

Type RM Length L Ch R = 1 ,3400    ,336.8,336.8,336.8
XS GIS Cut Line= 3
2379956.04087022597096.9022300942379393.93164575597072.560309717
2378964.45113293596947.863070851
#Sta/Elev= 30
       0 2792.46     9.3 2789.11    29.3 2775.06  125.742719.113   153.4 2707.23
   217.5 2669.93   261.5 2650.61   329.6 2608.38   345.6 2605.17   361.6 2607.22
   385.7 2612.14   409.7 2609.72   430.3 2619.28   469.7 2644.49   505.8 2662.74
   529.8 2683.47   557.8  2694.9   574.3 2711.53   603.4 2728.08   653.4 2741.48
     669 2740.77   720.1 2749.21     757 2760.45     770 2766.95   805.5 2774.31
   849.2 2787.97   865.8 2798.75   890.8 2810.25   928.8 2820.97  1009.9  2849.8
#Mann= 4 ,-1 , 0
       0     .06       0  125.74      .1       0   329.6    .045       0
   361.6      .1       0
Bank Sta=329.6,361.6
XS Rating Curve= 0 ,0
Exp/Cntr=0.3,0.1

Type RM Length L Ch R = 1 ,3063    ,256.8,256.8,256.8
XS GIS Cut Line= 3
2379793.66708401596672.4892504052379280.48775283 596840.54364251
2379000.02592591      596841.568
#Sta/Elev= 30
       0 2770.92    11.5 2758.71    13.7 2757.63   31.162756.241      41  2753.8
      62 2736.02   131.72695.408     243 2626.64   285.1 2603.71   293.5 2601.24
   301.9 2601.97   310.3  2598.8     320 2597.82   343.5 2596.43   359.3  2598.3
   407.1 2639.24   415.6  2644.8   478.7 2693.97   505.2 2716.85   537.6 2747.02
   555.4 2758.39   597.7 2775.97   645.7 2788.42   665.7 2797.46   677.7 2805.19
   689.7 2806.22   697.7 2808.94   717.7 2808.69   753.7 2815.38   820.5 2823.86
#Mann= 5 ,-1 , 0
       0      .1       0   31.16     .06       0   131.7      .1       0
     320    .045       0   359.3      .1       0
Bank Sta=320,359.3
XS Rating Curve= 0 ,0
Exp/Cntr=0.3,0.1

Type RM Length L Ch R = 1 ,2806    ,353.6,353.6,353.6
XS GIS Cut Line= 2
2379680.67765567596416.4120823892378973.03460466596777.554107085
#Sta/Elev= 30
       0 2759.91    15.2  2748.4    29.1 2732.74      33 2729.91    58.3 2726.46
    78.5 2710.04  101.182695.479   154.9 2663.22   181.8 2645.41   205.5 2626.74
   246.4 2590.21     253 2587.97   267.1 2587.43   279.8 2589.69   312.5 2590.89
   322.2 2592.36     339 2588.77   351.2 2591.09   425.5 2624.12     482 2654.18
   503.2    2663   527.6 2675.61   618.8 2708.39   642.6 2727.08   663.4 2733.95
   674.2 2740.24   693.8 2747.15   765.6 2781.58   782.3 2787.79   794.5 2794.03
#Mann= 4 ,-1 , 0
       0     .06       0  101.18      .1       0   246.4    .045       0
   279.8      .1       0
#XS Ineff= 2 , 0
                          325.27          2592.4
Permanent Ineff=
       F       F
Bank Sta=246.4,279.8
XS Rating Curve= 0 ,0
Exp/Cntr=0.3,0.1

Type RM Length L Ch R = 1 ,2453    ,453.7,453.7,453.7
XS GIS Cut Line= 3
2379628.37123887596254.1123212552379239.03209231596319.157477732
 2378905.6107002596721.750380567
#Sta/Elev= 30
       0 2772.65    12.5 2763.15    34.1 2751.04   102.9 2724.86   126.1  2710.8
  133.232709.125   175.8 2704.36   220.6 2686.43   263.9 2673.19   321.8 2666.68
   354.5 2659.28   370.4 2657.62   386.9 2650.37  395.462639.439   401.5    2634
   454.4 2613.98   513.8 2582.21   524.2 2579.59   573.7 2575.22   581.4 2573.33
   596.9 2573.06   607.8 2575.37   617.7 2585.03   644.7    2603   718.6 2644.84
   752.6 2667.04   790.3 2687.51   840.8 2719.23   883.4 2754.63   917.5 2773.75
#Mann= 5 ,-1 , 0
       0      .1       0  133.23     .06       0  395.46      .1       0
   573.7    .045       0   607.8      .1       0
Bank Sta=573.7,607.8
XS Rating Curve= 0 ,0
Exp/Cntr=0.3,0.1

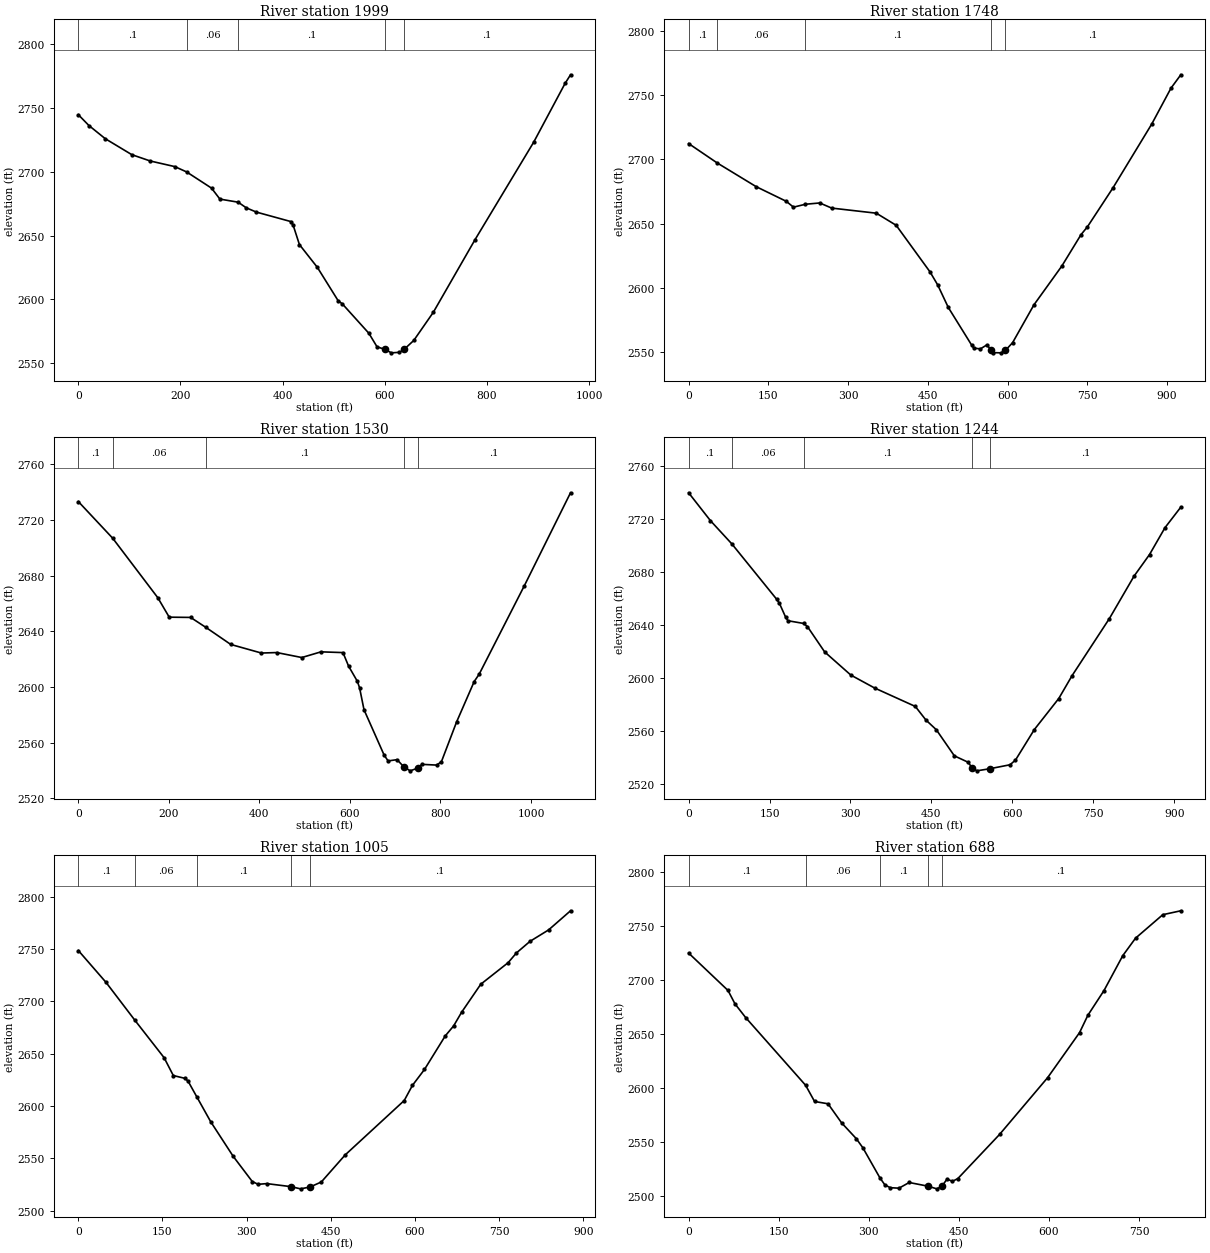
Type RM Length L Ch R = 1 ,1999    ,250.9,250.9,250.9
XS GIS Cut Line= 2
 2379491.4507166596180.931154858     2378527.877      596158.462
#Sta/Elev= 30
       0 2744.83    20.7 2736.35    52.7 2726.01   104.7 2713.47   140.7 2708.52
   188.8 2704.11  212.012699.934   260.8 2687.22   277.2  2678.6  313.032676.166
   328.8 2671.75   348.8 2668.38   416.5 2660.93   420.8 2657.95   432.9 2642.93
     468 2625.05   508.8 2598.82   516.8 2596.44   568.9 2573.31   584.9 2562.67
   600.8  2560.6   612.9 2557.94   628.9 2558.34   637.7 2560.58   656.9 2567.69
   695.1 2589.75   776.8 2646.76   891.7 2723.29   953.1 2769.37   963.8 2776.17
#Mann= 5 ,-1 , 0
       0      .1       0  212.01     .06       0  313.03      .1       0
   600.8    .045       0   637.7      .1       0
Bank Sta=600.8,637.7
XS Rating Curve= 0 ,0
Exp/Cntr=0.3,0.1

Type RM Length L Ch R = 1 ,1748    ,217.9,217.9,217.9
XS GIS Cut Line= 3
2379442.21958644596122.490107085 2379083.0358666595938.458690283
     2378564.385      595878.136
#Sta/Elev= 30
       0 2712.23   53.552697.186   127.1 2678.68   183.6 2667.31   197.2 2662.74
  219.622665.001   246.6 2666.01   269.1 2662.02     353 2658.05   390.4 2648.62
     454 2612.39   468.4 2602.29   488.4 2584.71   532.7 2555.18   536.9 2553.03
   548.8  2552.5   560.9 2555.58   568.5 2551.84     573 2549.56   587.4 2549.41
   595.8 2551.31   609.3  2557.3   649.5 2586.77   701.9 2616.92   738.1  2641.4
   750.2 2647.53   798.5 2678.01     871 2727.37   907.2 2755.31   925.7 2765.73
#Mann= 5 ,-1 , 0
       0      .1       0   53.55     .06       0  219.62      .1       0
   568.5    .045       0   595.8      .1       0
Bank Sta=568.5,595.8
XS Rating Curve= 0 ,0
Exp/Cntr=0.3,0.1

Type RM Length L Ch R = 1 ,1530    ,286.4,286.4,286.4
XS GIS Cut Line= 3
     2379684.301      596089.461  2379128.810117 595893.44751073
     2378844.688       595484.03
#Sta/Elev= 30
       0 2733.32      762706.931   175.6 2664.19   200.8 2650.22   248.1 2650.04
   281.92642.851   336.7 2630.62   404.4 2624.44   438.5 2624.78   493.7 2621.21
   536.1  2625.3   584.7 2624.76     597 2615.07   616.5 2604.07   621.4 2599.37
   631.1 2583.72   675.7 2550.99   684.4 2546.89   704.2  2547.8     719 2542.66
   733.2 2539.76   750.1 2541.77   759.1 2544.42   791.8 2543.89   802.2 2546.36
   835.6 2574.83   874.6 2603.97   885.6 2609.26   985.6 2672.97  1087.4 2739.64
#Mann= 5 ,-1 , 0
       0      .1       0      76     .06       0   281.9      .1       0
     719    .045       0   750.1      .1       0
Bank Sta=719,750.1
XS Rating Curve= 0 ,0
Exp/Cntr=0.3,0.1

Type RM Length L Ch R = 1 ,1244    ,239,239,239
XS GIS Cut Line= 3
     2379731.534      596066.4822379350.16687976595890.006474495
2379240.91596377595410.358808907
#Sta/Elev= 30
       0 2739.88    40.5 2718.77    80.22701.189     163 2659.47   168.4  2656.2
     180 2645.64   184.1 2643.13  212.992641.098   220.2 2638.72   252.1 2619.57
   300.6 2602.06   344.7 2592.27   420.2 2578.32   439.8 2568.06   459.1 2560.71
   492.5 2540.98   517.8 2536.17   525.7 2531.83   534.2 2529.64   558.8 2531.28
   595.7 2534.23   605.8 2537.78   640.8 2560.89     686 2584.33   710.6 2601.57
   779.9 2644.82   825.5 2676.83   854.2 2693.16   882.9  2713.5   912.2 2729.02
#Mann= 5 ,-1 , 0
       0      .1       0    80.2     .06       0  212.99      .1       0
   525.7    .045       0   558.8      .1       0
Bank Sta=525.7,558.8
XS Rating Curve= 0 ,0
Exp/Cntr=0.3,0.1

Type RM Length L Ch R = 1 ,1005    ,316.9,316.9,316.9
XS GIS Cut Line= 3
     2379792.304      596027.375      2379550.93      595705.388
     2379279.688      595315.541
#Sta/Elev= 30
       0 2748.43    49.3 2718.03  100.552681.973   152.9 2646.03   169.3 2629.01
   190.6 2626.26   195.8 2623.43  211.032608.783     236 2584.84     276 2551.88
     310 2527.81   320.5 2525.12   335.8 2525.81   378.6 2522.93   396.1 2520.81
     413 2522.56   433.1 2527.35   475.7 2553.23   580.9 2605.16   595.5 2619.61
     617 2634.83     654 2666.86   668.9 2676.38   683.2 2689.49   717.3 2716.21
   766.1 2736.81   780.9 2746.12     805 2757.14   838.3 2768.13   877.3 2786.37
#Mann= 5 ,-1 , 0
       0      .1       0  100.55     .06       0  211.03      .1       0
   378.6    .045       0     413      .1       0
Bank Sta=378.6,413
XS Rating Curve= 0 ,0
Exp/Cntr=0.3,0.1

Type RM Length L Ch R = 1 ,688     ,302.5,302.5,302.5
XS GIS Cut Line= 2
     2380052.996      595624.703     2379324.998      595248.296
#Sta/Elev= 30
       0 2724.85    65.6 2690.24    77.2 2677.85      95 2665.17  194.862602.509
   209.7 2587.56   232.2  2585.4   254.7 2567.81   279.1 2553.22   290.1 2544.76
   318.52516.938   326.8 2510.39   335.8  2507.8   350.3 2507.34   367.3  2512.6
   398.8 2509.17   413.3 2506.73   421.5 2508.96   430.3 2515.72   439.4 2513.69
   448.3 2516.23   517.8 2557.06   597.8 2609.57     651 2651.25   664.9 2667.35
   691.7 2690.17     723 2722.48   744.2  2738.6   789.6 2760.34   819.6 2763.96
#Mann= 5 ,-1 , 0
       0      .1       0  194.86     .06       0   318.5      .1       0
   398.8    .045       0   421.5      .1       0
Bank Sta=398.8,421.5
XS Rating Curve= 0 ,0
Exp/Cntr=0.3,0.1

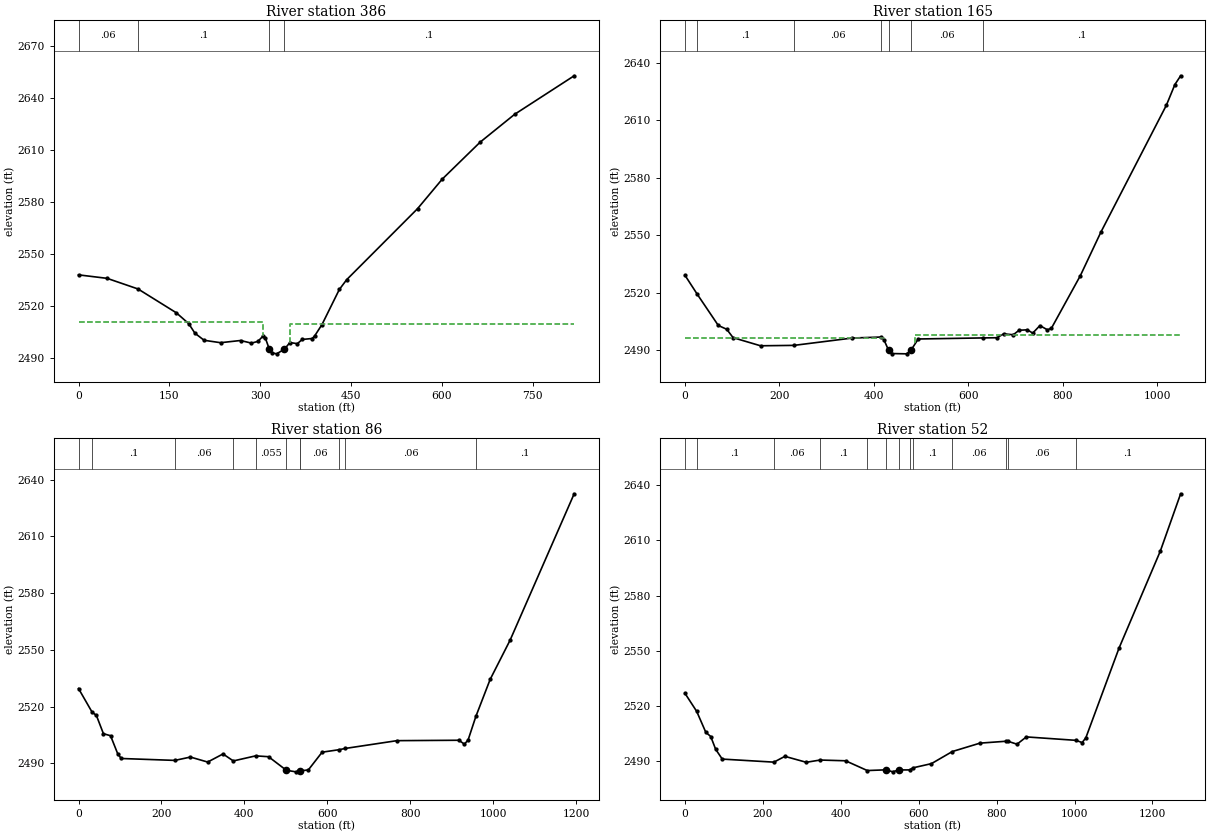
Type RM Length L Ch R = 1 ,386     ,220.1,220.1,220.1
XS GIS Cut Line= 2
2380129.08005123595228.5263000512379326.42778002595068.250252236
#Sta/Elev= 30
       0 2538.16    47.2 2536.15   98.292530.015   161.5 2516.27   181.9 2510.03
   192.2 2504.49   207.4 2500.39   234.6    2499   267.5 2500.27   285.6 2498.75
   296.1 2499.75   304.2 2502.61   308.3 2501.94   314.8 2495.54   319.6 2493.14
   327.1 2492.57     340 2495.22   349.1 2499.11   361.3 2498.43   369.5 2500.88
   385.8 2501.42   389.9 2502.87   402.1  2509.5   430.7 2529.72   442.9  2535.4
   559.9 2576.38   600.7 2593.45   663.2 2614.75   720.3 2630.86 818.498 2653.08
#Mann= 4 ,-1 , 0
       0     .06       0   98.29      .1       0   314.8    .045       0
     340      .1       0
#XS Ineff= 2 , 0
          304.13 2510.98  349.14         2509.83
Permanent Ineff=
       F       F
Bank Sta=314.8,340
XS Rating Curve= 0 ,0
Exp/Cntr(USF)=0,0
Exp/Cntr=0.5,0.3

Type RM Length L Ch R = 1 ,165     ,79.5,79.5,79.5
XS GIS Cut Line= 4
2380163.72767639 595214.049684042380054.96892966594996.362586293
 2379585.8010807594886.8547539772379287.58021572595015.471335557
#Sta/Elev= 30
       0 2529.07   26.082519.146    70.6 2502.87    88.5 2500.87   101.9  2496.5
     160 2492.26  230.84 2492.47   354.5 2496.31  416.062496.832   421.3 2495.48
   431.2 2489.96   437.9  2488.2   469.5 2488.05   478.6 2489.92   494.1 2495.81
  630.832496.365     661 2496.46   674.9 2498.48   695.4 2498.03   707.7 2500.36
   725.2  2500.6   736.6 2498.88   751.8 2502.81   767.7  2500.6   776.2 2501.42
   837.4 2528.85   880.9 2551.58  1019.7 2617.91  1037.7  2628.71049.896 2633.29
#Mann= 7 ,-1 , 0
       0     .06       0   26.08      .1       0  230.84     .06       0
  416.06      .1       0   431.2    .045       0   478.6     .06       0
  630.83      .1       0
#XS Ineff= 2 , 0
          421.79  2496.5  488.06          2497.7
Permanent Ineff=
       F       F
Bank Sta=431.2,478.6
XS Rating Curve= 0 ,0
Exp/Cntr(USF)=0,0
Exp/Cntr=0.5,0.3

Type RM Length L Ch R = 1 ,86      ,33.5,33.5,33.5
XS GIS Cut Line= 4
2380205.56339963595215.0673097412380096.29584005594929.368894349
2379631.49530139594817.1756608792379259.42590467594993.479313476
#Sta/Elev= 30
       0 2529.56      332516.964      43 2515.39    60.1 2505.65    77.3 2504.58
    94.4 2495.13     103 2492.53  232.492491.524     270 2493.29   311.6 2490.65
   348.6 2494.93  373.482491.237  427.292493.919   458.4 2493.48   501.5 2486.28
   524.7 2485.47   533.8    2486  535.022486.002   554.4 2486.47   587.7 2495.87
  629.352497.207  642.742497.821   768.3 2501.97   917.7 2502.18   930.9 2500.12
   939.8 2502.28   958.62514.779   993.1 2534.39  1041.2 2555.141195.756 2632.59
#Mann= 11 ,-1 , 0
       0     .06       0      33      .1       0  232.49     .06       0
  373.48      .1       0  427.29    .055       0   501.5    .045       0
   533.8    .055       0  535.02     .06       0  629.35      .1       0
  642.74     .06       0   958.6      .1       0
Bank Sta=501.5,533.8
XS Rating Curve= 0 ,0
Exp/Cntr(USF)=0,0
Exp/Cntr=0.5,0.3

Type RM Length L Ch R = 1 ,52      ,,,
XS GIS Cut Line= 4
2380224.48246064595209.445818168 2380122.7198906594913.062332923
2379628.48078877594777.4758053682379223.39317786594965.215650069
#Sta/Elev= 30
       0 2526.89   30.092517.084    53.5 2505.69    66.1 2503.43    78.8 2496.46
    95.7 2491.15  228.232489.492   256.5 2492.64   311.4 2489.41  346.852490.639
   412.3 2490.23  467.982484.922   516.9 2485.32   533.2 2484.22   548.4 2485.25
  577.172485.273  584.992486.383   632.7 2488.68  686.362495.266   757.2 2499.82
  823.132500.835  829.932500.782   852.3 2499.24   876.3 2503.21 1003.522501.343
  1019.5 2500.14    1029 2502.71  1114.3 2551.53  1220.2 2604.221272.344 2635.38
#Mann= 13 ,-1 , 0
       0     .06       0   30.09      .1       0  228.23     .06       0
  346.85      .1       0  467.98    .055       0   516.9    .045       0
   548.4    .055       0  577.17     .06       0  584.99      .1       0
  686.36     .06       0  823.13      .1       0  829.93     .06       0
 1003.52      .1       0
Bank Sta=516.9,548.4
XS Rating Curve= 0 ,0
Exp/Cntr(USF)=0,0
Exp/Cntr=0.3,0.1
LCMann Table=0

Chan Stop Cuts=-1
Use User Specified Reach Order=0
Composite Channel Slope=5